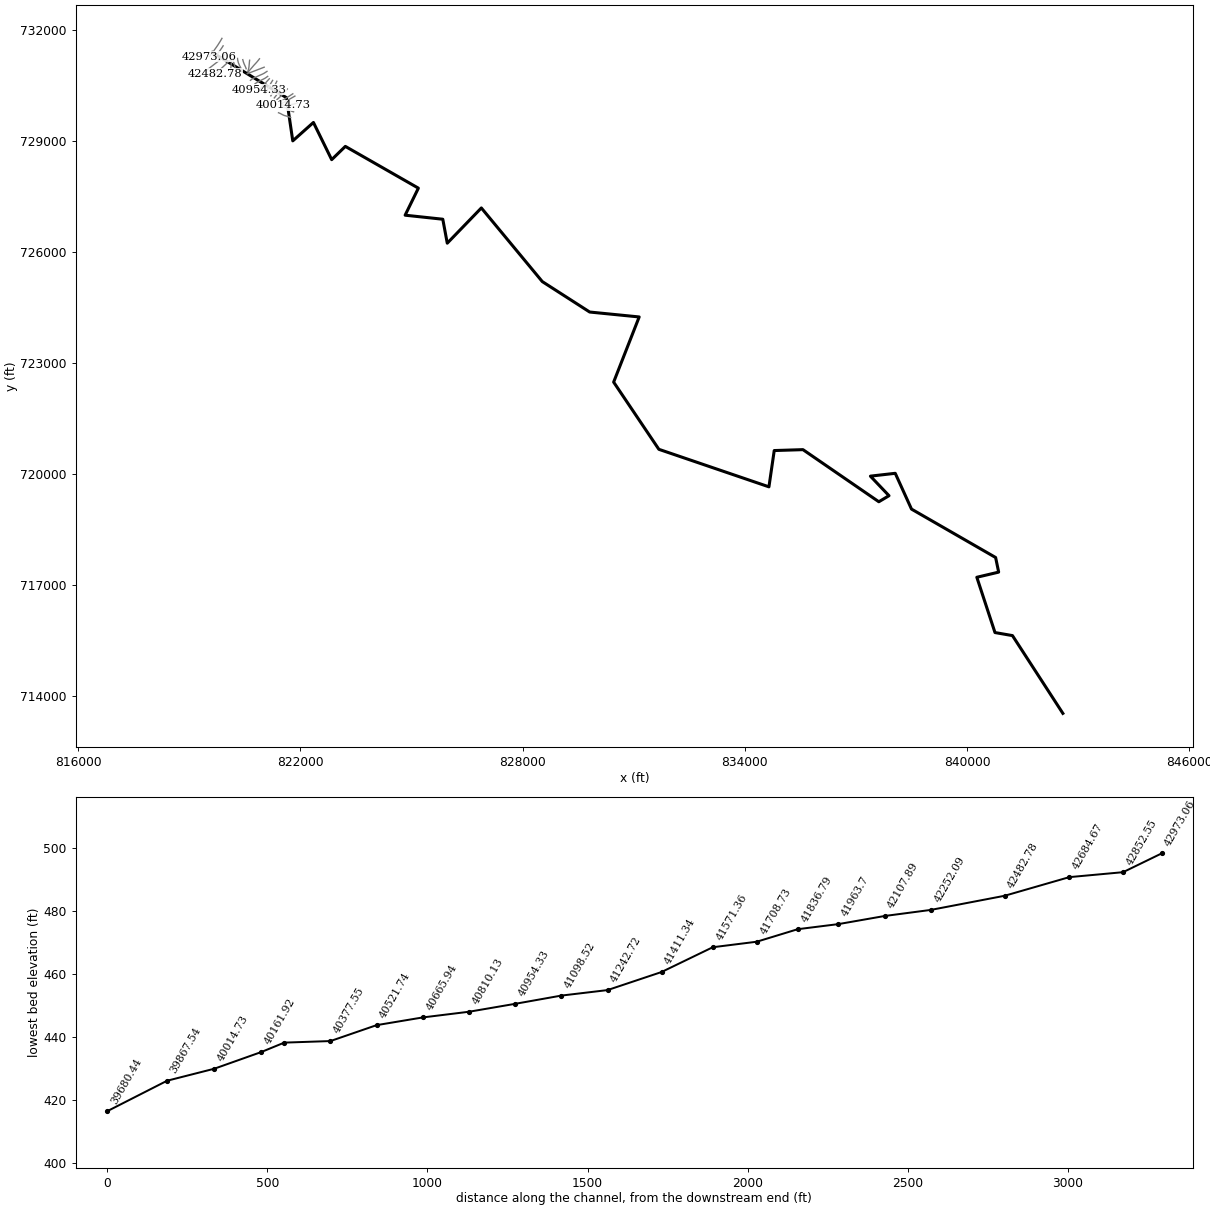
--- 7690_ras.prj (project) ---

Proj Title=7690
Current Plan=p01
Default Exp/Contr=0.3,0.1
English Units
Geom File=g01
Flow File=f01
Plan File=p01
Y Axis Title=Elevation
X Axis Title(PF)=Main Channel Distance
X Axis Title(XS)=Station
BEGIN DESCRIPTION:
RFD model 7690 exported to HEC-RAS
END DESCRIPTION:

--- 7690_ras.p01 (plan) ---

Plan Title=Plan 01
Program Version=4.10
Short Identifier=Plan 01
Geom File=g01
Flow File=f01
Subcritical Flow
Calc Critical at every XS
Secant Critical Depth

--- 7690_ras.f01 (steady flow) ---

Flow Title=Flow 01
Program Version=5.01
Number of Profiles= 6
Profile Names=10yr,25yr,50yr,100yr,100plus,500yr
River Rch & RM=7690,116,42973.06
 3809.77  5173.3 6401.36 7825.6911483.43 12103.1
River Rch & RM=7690,116,42852.55
 3812.16 5177.14 6406.52 7832.3811493.2512114.44
River Rch & RM=7690,116,42684.67
 3815.75  5182.9 6414.25 7842.4211507.9912131.44
River Rch & RM=7690,116,42482.78
 3817.75  5186.1 6418.54    784811516.1712140.89
River Rch & RM=7690,116,42252.09
  4934.5 7022.16  8916.2 11127.616328.6617794.15
River Rch & RM=7690,116,42107.89
 4936.52 7025.55 8920.8711133.7916337.7417804.99
River Rch & RM=7690,116, 41963.7
 4940.55 7032.33 8930.2111146.1716355.9117826.66
River Rch & RM=7690,116,41836.79
 4968.72 7079.72 8995.4811232.7316482.93 17978.3
River Rch & RM=7690,116,41708.73
  4971.4 7084.22 9001.6811240.9716495.0217992.73
River Rch & RM=7690,116,41571.36
  4973.4  7087.6 9006.3411247.1516504.0818003.55
River Rch & RM=7690,116,41411.34
 5034.37 7190.33    914811435.1616779.9818333.33
River Rch & RM=7690,116,41242.72
 5040.67 7200.97 9162.6711454.6516808.5718367.53
River Rch & RM=7690,116,41098.52
 5054.25 7223.89  9194.311496.6616870.22 18441.3
River Rch & RM=7690,116,40954.33
 5058.55 7231.15 9204.3211509.9716889.7618464.69
River Rch & RM=7690,116,40810.13
 5062.85 7238.41 9214.3411523.2916909.2918488.07
River Rch & RM=7690,116,40665.94
 5065.16 7242.31 9219.7311530.45 16919.818500.65
River Rch & RM=7690,116,40521.74
 5074.08 7257.38 9240.5311558.0816960.35 18549.2
River Rch & RM=7690,116,40377.55
 5096.49 7295.26 9292.8411627.6117062.3718671.39
River Rch & RM=7690,116,40233.35
 5098.13 7298.04 9296.6811632.7117069.8718680.38
River Rch & RM=7690,116,40161.92
  5101.1 7303.04  9303.611641.9117083.3618696.54
River Rch & RM=7690,116,40014.73
 5122.12  7338.6 9352.7411707.2417179.2318811.45
River Rch & RM=7690,116,39867.54
 5123.43 7340.83 9355.8111711.3217185.2118818.63
River Rch & RM=7690,116,39680.44
 5126.71 7346.38 9363.4811721.5217200.1818836.57
River Rch & RM=7690,116,39425.97
 5188.74 7451.49 9508.8611914.9517484.0219177.16
River Rch & RM=7690,116,39278.78
 5192.32 7457.56 9517.2511926.1317500.4219196.86
River Rch & RM=7690,116,39119.58
 5195.24 7462.52 9524.1211935.2717513.8319212.97
River Rch & RM=7690,116,38795.87
 5299.18 7639.19 9768.8812261.3717992.3619788.46
River Rch & RM=7690,116,38542.82
 5307.19 7652.84  9787.812286.6118029.3919833.05
River Rch & RM=7690,116,38351.43
 5309.44 7656.66  9793.112293.6718039.7619845.54
River Rch & RM=7690,116,38049.37
 5317.12 7669.75 9811.2612317.8918075.2919888.34
River Rch & RM=7690,116,37806.86
 5319.68 7674.11 9817.3112325.9618087.13 19902.6
River Rch & RM=7690,116,37659.67
 5321.28 7676.83 9821.09   1233118094.5319911.52
River Rch & RM=7690,116,37512.48
 5322.88 7679.56 9824.8712336.0418101.9319920.43
River Rch & RM=7690,116,37365.29
 5326.71  7686.1 9833.9412348.1418119.6819941.82
River Rch & RM=7690,116,37190.31
 5330.23 7692.09 9842.2512359.2318135.9619961.43
River Rch & RM=7690,116,37018.42
 5332.46  7695.9 9847.5412366.2918146.3119973.91
River Rch & RM=7690,116,36723.75
 5353.19 7731.25 9896.6112431.7518242.3820089.71
River Rch & RM=7690,116,36187.76
 5748.14 8409.42 10841.413696.2120097.8422337.37
River Rch & RM=7690,116, 35916.4
 5751.48 8415.1910849.4713707.0420113.7322356.71
River Rch & RM=7690,116,35746.19
 5756.33 8423.5910861.21 13722.820136.8622384.85
River Rch & RM=7690,116,   35599
 5886.19  8648.511176.0614145.7720757.5223141.35
River Rch & RM=7690,116,35474.85
 5903.82 8679.1111218.9514203.4520842.1623244.68
River Rch & RM=7690,116,35304.61
 6020.95 8882.8711504.8614588.2821406.8723935.11
River Rch & RM=7690,116,35239.36
 6022.13 8884.9211507.7414592.1721412.5823942.09
River Rch & RM=7690,116,35005.51
 6025.37 8890.5711515.6714602.8521428.2523961.28
River Rch & RM=7690,116,34771.66
 6036.85 8910.5711543.7814640.7221483.8124029.31
River Rch & RM=7690,116,34537.81
 6040.67 8917.2411553.1414653.3321502.3324051.99
River Rch & RM=7690,116,34303.96
 6059.76 8950.5311599.9314716.3821594.8424165.31
River Rch & RM=7690,116,34104.72
 6062.69 8955.6511607.1214726.0821609.0724182.74
River Rch & RM=7690,116,33592.48
 6193.72 9184.7311929.4315160.8722247.0824965.55
River Rch & RM=7690,116, 33340.8
 6201.24 9197.8911947.98 15185.922283.8225010.69
River Rch & RM=7690,116,33134.71
  6202.1 9199.4111950.1215188.7922288.06 25015.9
River Rch & RM=7690,116,33055.61
 6203.26 9201.4411952.9715192.6422293.7125022.84
River Rch & RM=7690,116,32842.33
 6269.75 9318.0412117.3215414.6522619.4825423.46
River Rch & RM=7690,116,32561.69
 6276.34 9329.6212133.6415436.7222651.8725463.31
River Rch & RM=7690,116,32276.55
 6287.51 9349.2412161.3115474.1222706.7525530.87
River Rch & RM=7690,116,32067.77
  6408.4 9561.9412461.6415880.3923302.9126265.67
River Rch & RM=7690,116, 31820.8
 6415.19 9573.8912478.5415903.2623336.4726307.09
River Rch & RM=7690,116,31533.02
 6420.55 9583.3512491.9115921.3723363.0426339.88
River Rch & RM=7690,116,30784.22
 6433.25 9605.7412523.5615964.2223425.9326417.52
River Rch & RM=7690,116,30274.41
  6533.1 9782.11 12773.116302.3723922.1227030.76
River Rch & RM=7690,116,30092.08
 6537.29 9789.5112783.5816316.5823942.9827056.57
River Rch & RM=7690,116,29845.12
 6544.82 9802.8312802.4516342.1623980.5127103.01
River Rch & RM=7690,116,29686.22
 6548.16 9808.7512810.8316353.5223997.1927123.64
River Rch & RM=7690,116,29598.15
 6549.83  9811.712815.02 16359.224005.5327133.96
River Rch & RM=7690,116,29507.97
 6550.39 9812.6912816.41 16361.1 24008.3 27137.4
River Rch & RM=7690,116,29349.06
 6799.3810254.7813443.7517213.15 25258.628688.48
River Rch & RM=7690,116,29116.48
 6831.9410312.8113526.2717325.4225423.35 28893.4
River Rch & RM=7690,116,28875.64
 6838.44 10324.413542.7617347.8525456.2728934.37
River Rch & RM=7690,116,28634.81
 6841.1510329.2313549.63 17357.225469.9828951.43
River Rch & RM=7690,116,28393.97
 6848.4510342.2613568.1617382.42   2550728997.51
River Rch & RM=7690,116,28153.13
 6851.9710348.5313577.0917394.5725524.8229019.69
River Rch & RM=7690,116, 27912.3
 6855.48 10354.813586.0117406.7125542.6329041.87
River Rch & RM=7690,116,27671.46
 6976.4110570.8913893.7417825.8526157.6829808.37
River Rch & RM=7690,116,27430.62
 6983.0810582.8413910.7717849.0726191.7529850.89
River Rch & RM=7690,116,27189.79
 6985.2210586.6613916.22 17856.526202.6629864.49
River Rch & RM=7690,116,26948.95
 6997.4910608.6313947.55 17899.226265.32 29942.7
River Rch & RM=7690,116,26708.11
 7000.6910614.3613955.7117910.3426281.66 29963.1
River Rch & RM=7690,116,26467.28
 7010.2810631.5413980.2117943.7426330.6830024.28
River Rch & RM=7690,116,26226.44
 7012.6810635.8413986.3317952.0926342.9330039.57
River Rch & RM=7690,116, 25985.6
 7216.7911002.4614509.9118666.8427391.7631351.48
River Rch & RM=7690,116,25744.77
 7221.76 11011.414522.6918684.3127417.3931383.61
River Rch & RM=7690,116,25611.76
 7223.5811014.69 14527.418690.7527426.8431395.44
River Rch & RM=7690,116,25503.93
 7224.8911017.0414530.7618695.3427433.5831403.89
River Rch & RM=7690,116,25263.09
 7935.93 12308.916387.3421242.6631171.5236117.79
River Rch & RM=7690,116,25022.26
 7939.8612316.0916397.7221256.96 31192.5 36144.4
River Rch & RM=7690,116,24781.42
 7943.7812323.27 16408.121271.2531213.4736171.01
River Rch & RM=7690,116,24642.32
 7973.8912378.47 16487.821381.0431374.5736375.46
River Rch & RM=7690,116,24425.56
 7976.58 12383.416494.9221390.8531388.9736393.74
River Rch & RM=7690,116,23611.74
 7985.6212399.9816518.8821423.8531437.3936455.21
River Rch & RM=7690,116,22996.55
 8353.2413077.04 17499.222776.9833422.9838983.55
River Rch & RM=7690,116,22400.62
 8397.7313159.3417618.6722942.2133665.4539293.28
River Rch & RM=7690,116,21735.45
 8420.8613202.1617680.8623028.2433791.6939454.63
River Rch & RM=7690,116,20875.27
 8469.5713292.4317811.9823209.7234057.9839795.17
River Rch & RM=7690,116,20411.77
 9065.5314404.1519433.0525459.9137359.9244038.18
River Rch & RM=7690,116,20027.79
 9073.1614418.4719454.0125489.0837402.7244093.43
River Rch & RM=7690,116,19484.77
 9873.91 15933.321679.9728598.0841964.8850014.72
River Rch & RM=7690,116,18905.52
 9885.5715955.5321712.7828644.0642032.3550102.76
River Rch & RM=7690,116,18694.24
 9981.7116138.9821983.63 29023.842589.5850830.45
River Rch & RM=7690,116,18094.28
 9989.2916153.4622005.02 29053.8 42633.650887.97
River Rch & RM=7690,116,17630.78
10002.5516178.7822042.4329106.2842710.6150988.62
River Rch & RM=7690,116,16867.47
10015.1616202.8922078.0429156.2442783.9251084.45
River Rch & RM=7690,116,14312.13
10218.0716591.3522652.6329962.9943967.7552634.05
River Rch & RM=7690,116,13360.41
 10265.916683.1222788.5430154.0144248.0453001.53
River Rch & RM=7690,116,12234.78
10340.5516826.5323001.04 30452.8 44686.553576.81
River Rch & RM=7690,116,9300.415
 11390.818863.2926035.1634737.2150973.4561882.42
River Rch & RM=7690,116,8686.478
11423.7618927.7826131.7134874.0751174.2762149.39
River Rch & RM=7690,116,7375.502
11463.3819005.3626247.8735038.7751415.9662470.83
River Rch & RM=7690,116,7235.807
11465.6919009.8726254.6335048.3651430.0362489.55
River Rch & RM=7690,116,6698.386
11488.7219054.9926322.2135144.22 51570.7 62676.7
River Rch & RM=7690,116,4464.114
11587.6319248.9126612.8235556.5652175.7663482.28
River Rch & RM=7690,116,3843.233
11600.21 19273.626649.8635609.1352252.8963585.03
River Rch & RM=7690,116,3070.665
 11690.919451.7126917.0335988.4952809.5764327.07
River Rch & RM=7690,116,1939.797
11702.6519474.82 26951.736037.7452881.8464423.45
River Rch & RM=7690,116,988.0796
12842.6621734.9930359.7740897.2160012.6473993.11
River Rch & RM=7690,116,       0
12849.7821749.2430381.3540928.0960057.9674054.28
Boundary for River Rch & Prof#=7690,116,1
Up Type= 0
Dn Type= 2
Boundary for River Rch & Prof#=7690,116,2
Up Type= 0
Dn Type= 2
Boundary for River Rch & Prof#=7690,116,2
Up Type= 0
Dn Type= 2
Boundary for River Rch & Prof#=7690,116,2
Up Type= 0
Dn Type= 2
Boundary for River Rch & Prof#=7690,116,2
Up Type= 0
Dn Type= 2
Boundary for River Rch & Prof#=7690,116,2
Up Type= 0
Dn Type= 2

--- 7690_ras.g01 (geometry) ---

Geom Title=7690
Program Version=4.10

River Reach=7690,116
Reach XY= 30
819627.477612179731382.056473008821621.997927641730164.504655772
821793.854325228728997.397749947822351.600667796729494.297906512
822844.169542968728490.173010794 823212.99229796728848.557337277
825184.563478522727721.170184513824826.830003338726990.935138697
825843.634457714726882.222273627825964.244897166 726235.05283435
826884.605972782727186.618577026828529.763904501725198.921209943
829809.220470487724376.918734119831145.375461757724244.168550914
830455.828368685 722485.32145104831676.459029392 720671.03230411
834648.152580902719657.989833856834790.887525596720637.705659942
  835566.7136702720661.988724687837614.577690593719255.327364323
837889.099238933719419.007255301837387.254450737719946.647615079
838057.992418028720023.210610854838496.558527822719056.992221904
840767.233318615717750.243911364840849.711047959717355.501781819
840260.032072388717216.640403591840750.232477437 715724.28913663
841221.889867418715642.177128941842582.566950745713542.567753963

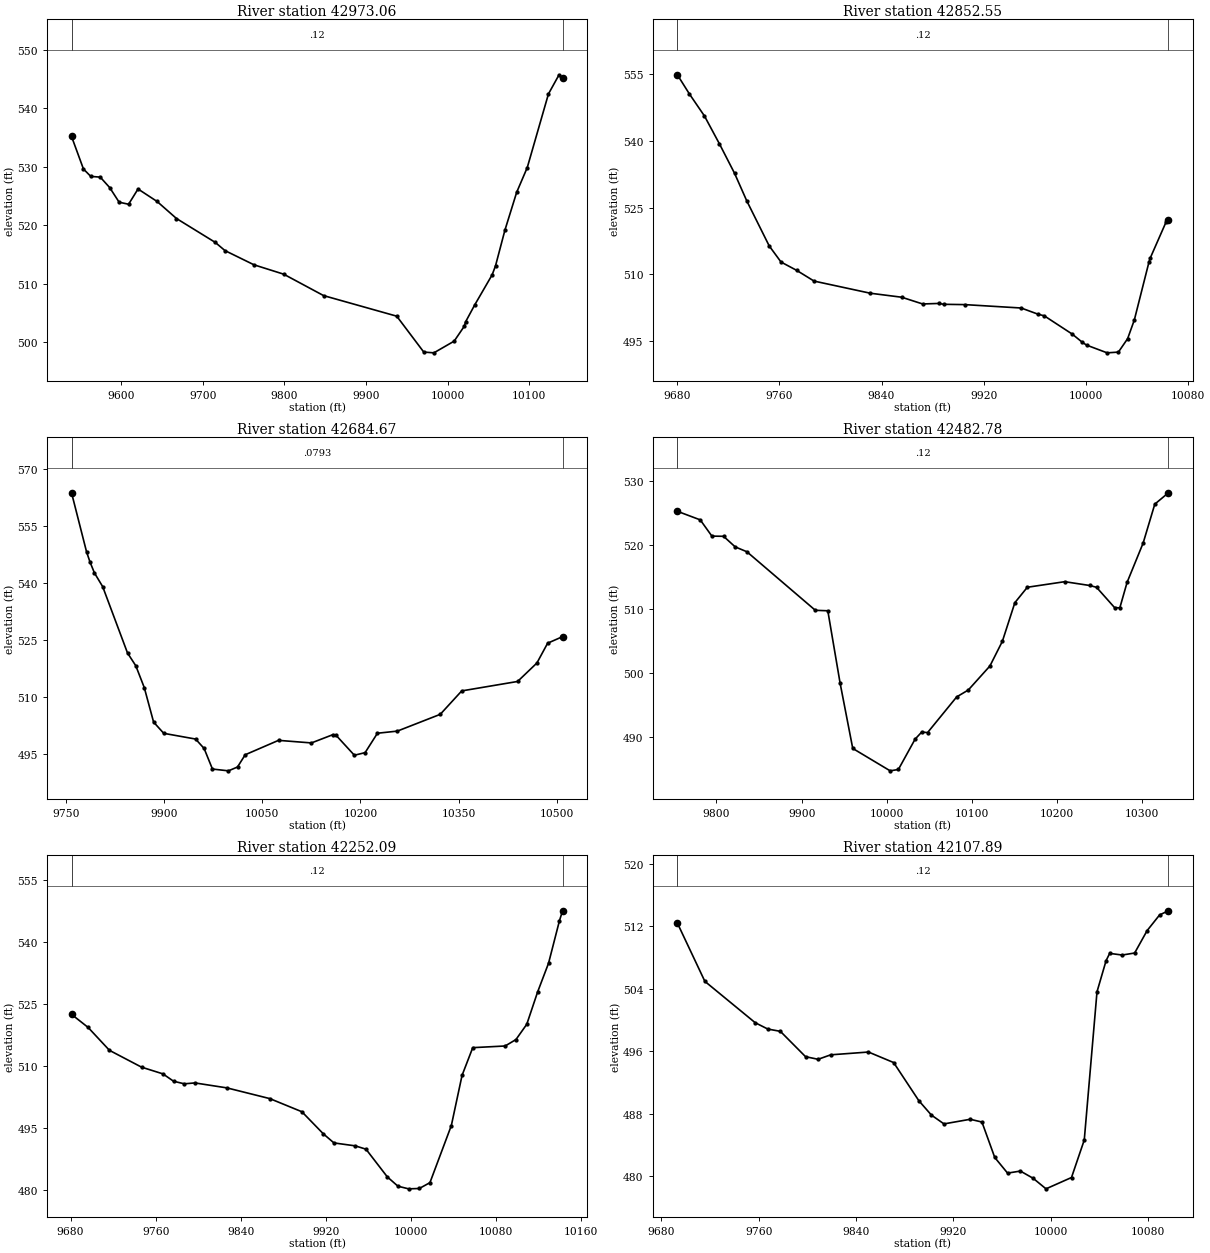
Type RM Length L Ch R = 1 ,42973.06,120.508700,120.508700,120.508700
XS GIS Cut Line= 6
819882.375788621731765.354962664819833.570371293 731681.76098081
819759.380226419731565.932439676819627.691120337731380.658469359
819600.765656843731345.131269078819540.012530111731271.682517348
#Sta/Elev= 30
9539.335535.16039553.964529.59339562.905528.33969574.485528.21679586.065526.4352
9597.644523.93469609.224523.58579620.803526.18769644.163524.05789667.913521.1485
9715.415517.07029727.291515.67299762.917513.24019799.269511.64289848.157 507.984
9937.737504.47189970.857 498.3429983.238498.2128 10008.1500.211110020.65502.7874
10022.01503.486110033.19 506.37510054.62511.533510058.73513.058910070.31519.1814
10084.68525.627810097.66529.855910123.61542.424510136.59545.6907 10140.9 545.203
#Mann= 3 , 0 , 0
9539.335    0.12       09539.335    0.12       0 10140.9    0.12       0
#XS Ineff= 2 , 0
       0                               0
Bank Sta=9539.335,10140.9
Exp/Cntr=0.3,0.1

Type RM Length L Ch R = 1 ,42852.55,167.882100,167.882100,167.882100
XS GIS Cut Line= 6
819913.889652199731563.030448102819888.801557005731522.550419607
819829.961138835731437.596675451819785.240664191731378.983957261
819709.592401852731292.758618935819673.650676892731265.884400909
#Sta/Elev= 30
9680.185554.90929689.633550.57839701.398 545.6259713.163539.32149724.927532.7276
9734.486526.51299752.049516.36389761.323512.72089773.487510.85979787.175508.4307
 9831.15505.69799855.815504.79219872.151503.2741 9884.73503.39419888.786503.2002
9905.249503.12869949.276 502.3659962.342500.9835 9967.38500.59599989.261496.4824
9997.036494.656910000.43494.009710016.53492.265610025.35492.431210032.57495.4526
10037.83 499.67410049.27512.704310050.32513.650210062.81521.834310064.49522.1947
#Mann= 3 , 0 , 0
9680.185    0.12       09680.185    0.12       010064.49    0.12       0
#XS Ineff= 2 , 0
       0                               0
Bank Sta=9680.185,10064.49
Exp/Cntr=0.3,0.1

Type RM Length L Ch R = 1 ,42684.67,201.890200,201.890200,201.890200
XS GIS Cut Line= 6
820000.849929997731393.984459351819940.725772541731312.790512042
819870.324482064 731229.15897187 819851.75240978731202.633343691
819838.563519576731189.987867483819450.448222878730891.092884729
#Sta/Elev= 30
9758.216563.8552 9781.16548.3357 9786.44545.65049793.246542.7638 9805.85539.1621
9843.836521.69879856.497518.34129869.478512.58589883.714503.52159899.242500.5648
9947.907499.06179960.979496.58199973.707491.16639998.202490.697610012.03491.7072
10023.82494.930710074.74498.717910125.07498.039610157.91500.216410162.99500.0056
10190.75494.800410207.17 495.48710226.03 500.59210256.43501.148410322.11505.5672
10354.95511.729410440.37514.211310469.89519.067810486.31 524.27910509.15526.0058
#Mann= 3 , 0 , 0
9758.216  0.0793       09758.216  0.0793       010509.15  0.0793       0
#XS Ineff= 2 , 0
       0                10101.92       0
Bank Sta=9758.216,10509.15
Exp/Cntr=0.3,0.1

Type RM Length L Ch R = 1 ,42482.78,230.696000,230.696000,230.696000
XS GIS Cut Line= 2
820124.637672481 731195.64849175819703.328552206730801.880570897
#Sta/Elev= 30
9754.062525.29099780.941523.95039794.629521.41599808.317521.38929822.004519.7338
9835.692518.97969916.107509.84189930.752509.76829945.194498.47499960.042488.2907
10003.98484.795510013.63485.007910033.27 489.74110041.01490.845910047.91490.7632
10082.07496.325210095.76497.408510121.14 501.15610135.78505.013910150.43511.0338
10165.07513.437910209.01 514.307 10238.3513.712510246.32513.431810267.59510.2544
 10273.7510.227610282.23514.203310301.07520.332410314.76526.403510330.74528.1781
#Mann= 3 , 0 , 0
9754.062    0.12       09754.062    0.12       010330.74    0.12       0
#XS Ineff= 2 , 0
       0                10143.67       0
Bank Sta=9754.062,10330.74
Exp/Cntr=0.3,0.1

Type RM Length L Ch R = 1 ,42252.09,144.195400,144.195400,144.195400
XS GIS Cut Line= 6
820146.892073071731210.477598831820119.720907462730942.743968619
820115.379066396  730874.8287754 820110.97791984 730835.63372985
820100.498425466730776.787820871820094.482643699730752.179959222
#Sta/Elev= 30
9680.862522.54959696.419519.39359716.522513.84059746.676 509.7749766.779508.1457
 9776.83506.35849786.881505.73729796.933505.95249827.087504.74539867.292502.1577
9897.446498.97769917.549493.6474  9927.6491.42949947.703490.71579957.733489.9128
9977.779483.20979987.802 480.9479997.825480.314910007.84480.397710017.86481.8118
10037.98495.637110048.05507.773810058.11514.490710088.59514.894310098.74516.4547
 10108.9520.146410119.08527.952210129.38534.926310139.67545.249610142.57547.6239
#Mann= 3 , 0 , 0
9680.862    0.12       09680.862    0.12       010142.57    0.12       0
#XS Ineff= 2 , 0
       0                               0
Bank Sta=9680.862,10142.57
Exp/Cntr=0.3,0.1

Type RM Length L Ch R = 1 ,42107.89,144.195400,144.195400,144.195400
XS GIS Cut Line= 6
820176.624893587731206.861316818 820237.62724346730974.158581852
820258.014043446730912.158864632820258.553614544730910.233023785
820271.730005297730867.870169005820283.081095346  730817.9566306
#Sta/Elev= 30
9693.169512.39229715.769504.9325 9757.12499.64169767.458498.83189777.796498.5374
9798.472495.2956 9808.81494.96079819.148495.53319850.161495.89049870.837494.5435
9891.513489.67049901.851487.82369912.189486.69479933.734487.28619943.375486.9343
9953.902482.39819964.429480.39819974.956480.66099985.482 479.7319996.009478.3863
10016.95479.835510027.43484.6322 10037.9503.599610045.36507.580410048.31508.5131
10058.56508.300710068.82508.558810079.07511.427210089.33513.433110096.55513.9633
#Mann= 3 , 0 , 0
9693.169    0.12       09693.169    0.12       010096.55    0.12       0
#XS Ineff= 2 , 0
       09872.882                       0
Bank Sta=9693.169,10096.55
Exp/Cntr=0.3,0.1

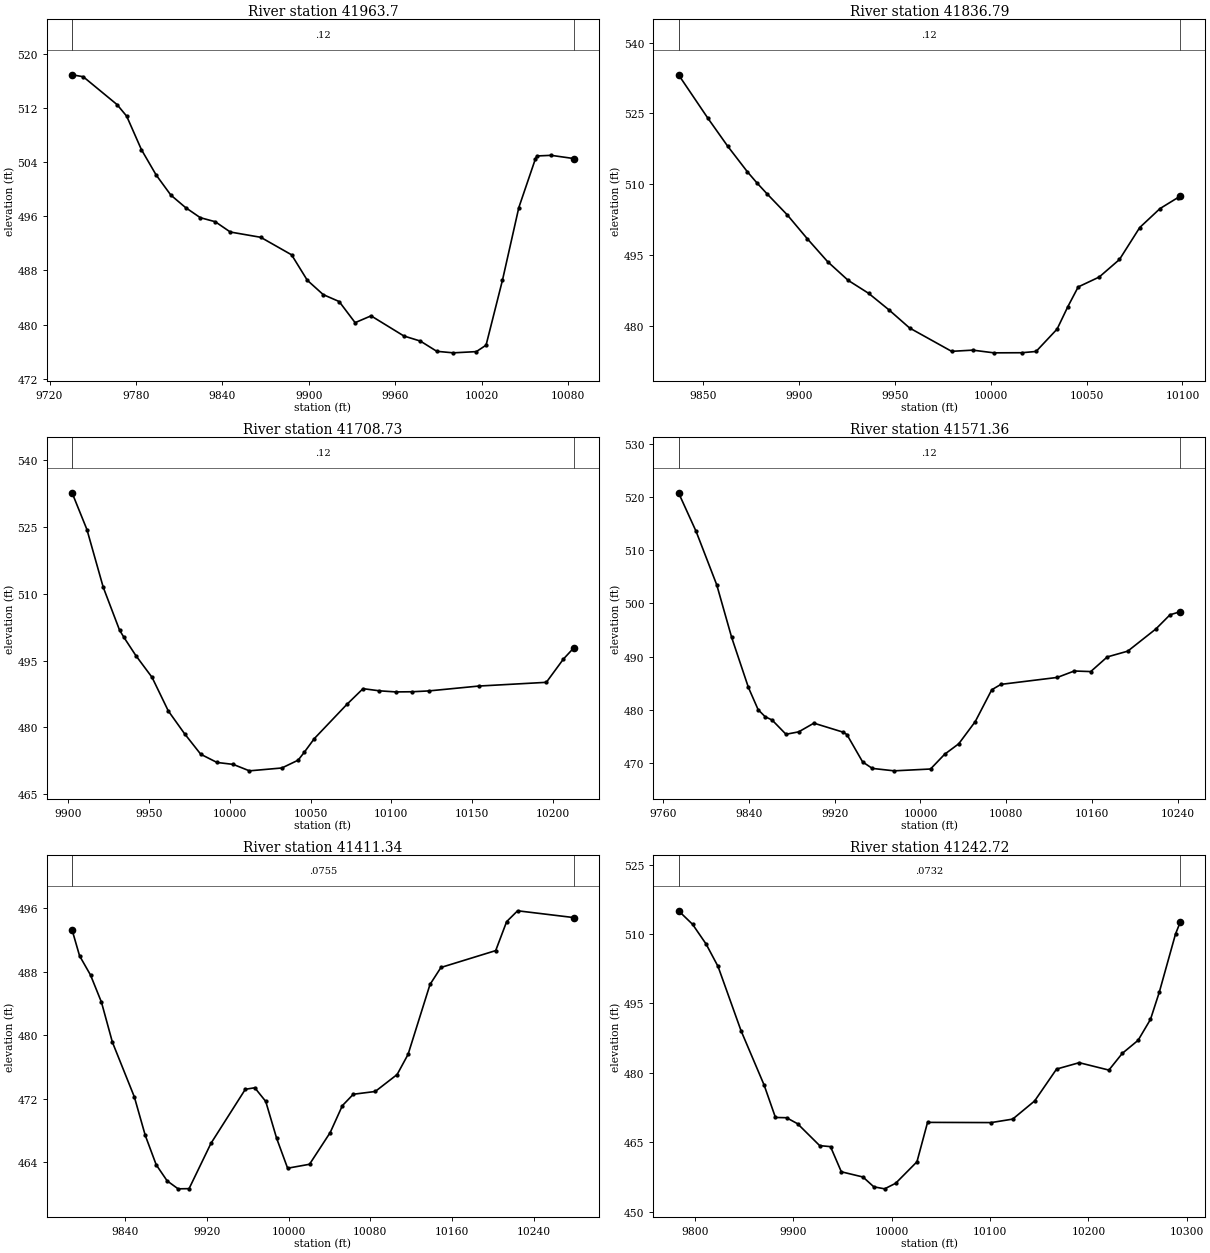
Type RM Length L Ch R = 1 , 41963.7,126.904400,126.904400,126.904400
XS GIS Cut Line= 6
820301.717484364731222.697576336820305.723756308731184.805299464
820326.189695459731101.993894439820360.629347175731023.312949534
820415.976026726730922.207091104820425.389018291730900.509527126
#Sta/Elev= 30
9735.628516.91549743.369516.62779766.848512.51219773.536510.79999783.759505.8577
9793.986502.10979804.213499.1312 9814.44497.28579824.667495.79459835.018495.1988
9845.492493.67559866.608492.89579888.037 490.3059898.913486.55039909.983 484.426
9921.054 483.4029932.124480.28049943.195481.28789965.986  478.319977.412477.5595
9988.838476.045710000.27475.8207 10016.3476.001510023.03476.9541 10034.4486.5454
10045.78497.298210057.15504.404410058.28504.916310068.18505.010910083.98504.5327
#Mann= 3 , 0 , 0
9735.628    0.12       09735.628    0.12       010083.98    0.12       0
#XS Ineff= 2 , 0
       0                               0
Bank Sta=9735.628,10083.98
Exp/Cntr=0.3,0.1

Type RM Length L Ch R = 1 ,41836.79,128.062200,128.062200,128.062200
XS GIS Cut Line= 6
820444.432906141731189.748767708820461.326554962731126.356335811
820481.926472463731071.880644933820496.833467143731039.767362028
820521.435456661730985.788652605820535.446982874730944.973033154
#Sta/Elev= 27
9837.169533.19259852.432524.00419862.781518.0606 9873.13512.58819878.205510.1945
9883.479507.87739893.828503.49949904.224498.46319914.915493.55619925.606489.5953
9936.297 486.8399946.988483.30339957.679479.48229979.605 474.5289990.618474.7826
10001.66474.209810016.11474.231910023.64474.500410034.63479.254210040.22484.0043
10045.62488.190810056.57490.286410067.15494.009810077.72500.792110088.29504.8108
10097.52507.114410098.89507.5257
#Mann= 3 , 0 , 0
9837.169    0.12       09837.169    0.12       010098.89    0.12       0
#XS Ineff= 2 , 0
       0                               0
Bank Sta=9837.169,10098.89
Exp/Cntr=0.3,0.1

Type RM Length L Ch R = 1 ,41708.73,137.368800,137.368800,137.368800
XS GIS Cut Line= 6
820629.116656621731174.118411417820623.678872418731132.045266653
820611.981687618730996.679390916820603.636049477730949.207234506
820593.094406171730908.455936036820579.449691789730868.906442619
#Sta/Elev= 27
9902.501532.67749911.695524.41759921.778511.46519931.861501.84999934.617500.1968
9941.944496.12939951.995 491.2269962.031483.69619972.067478.58919982.103473.9672
 9992.14472.125410002.18471.690710012.21470.241910032.29470.884210042.33472.6345
10046.06474.369210052.37477.481910072.44485.1414 10082.5 488.69310092.65488.2091
10102.81487.960710112.96488.000610123.11488.1852   10154 489.276 10195.9490.1169
10206.48495.351810212.92497.8657
#Mann= 3 , 0 , 0
9902.501    0.12       09902.501    0.12       010212.92    0.12       0
#XS Ineff= 2 , 0
       0                               0
Bank Sta=9902.501,10212.92
Exp/Cntr=0.3,0.1

Type RM Length L Ch R = 1 ,41571.36,160.023000,160.023000,160.023000
XS GIS Cut Line= 6
820894.773757797731213.639428627820869.050927141731178.871476177
820816.154987538731115.230935113820749.159965876731042.906894247
820745.675437047731039.194885982820590.710366539730857.692220032
#Sta/Elev= 30
9774.248520.83199790.681513.54569809.873503.52469823.834493.60469839.479484.1832
9848.537480.00739855.123478.6756 9861.54478.06439874.544475.37489886.412475.8325
9900.565477.46919927.827 475.775 9931.38475.32599946.095470.16419955.089468.9529
9975.526468.493810009.44468.838510022.59471.610710035.77473.586110051.17477.7607
10066.57483.752710075.19484.769810127.78486.076910143.57487.285410158.97487.1783
10174.37489.933510193.53491.024710219.83495.211710232.97497.867910242.58498.4507
#Mann= 3 , 0 , 0
9774.248    0.12       09774.248    0.12       010242.58    0.12       0
#XS Ineff= 2 , 0
       09928.502                       0
Bank Sta=9774.248,10242.58
Exp/Cntr=0.3,0.1

Type RM Length L Ch R = 1 ,41411.34,168.618600,168.618600,168.618600
XS GIS Cut Line= 2
821021.839429736 730986.23865273820563.629039212730808.875017434
#Sta/Elev= 30
9787.936493.2607 9795.27489.99079805.993487.57139816.716484.14819827.439479.1068
9848.885472.22879859.608467.37179870.331463.66549881.054461.64159891.777460.6394
  9902.5460.66419923.946466.37249957.581473.17819966.838 473.3719977.561471.6546
9988.284466.98929999.007463.236910020.45463.734510040.69467.730710052.62471.1217
10063.34472.553810084.79472.902410106.24475.039510116.96477.581910138.41486.3802
10149.13 488.52310202.74490.646410213.47494.296110224.19495.663210279.28494.8053
#Mann= 3 , 0 , 0
9787.936  0.0755       09787.936  0.0755       010279.28  0.0755       0
#XS Ineff= 2 , 0
       09961.041        10054.81       0
Bank Sta=9787.936,10279.28
Exp/Cntr=0.3,0.1

Type RM Length L Ch R = 1 ,41242.72,144.195400,144.195400,144.195400
XS GIS Cut Line= 6
821097.749705421730873.300942905821018.958299214730822.108389903
820978.048789779730800.928372211 820746.72800588730698.122348894
820697.763337704730667.850377004820651.378178364730631.428423194
#Sta/Elev= 30
9783.455515.02569797.712512.10229811.437507.84389823.608502.9869 9847.01489.0808
9870.412477.36559881.939470.34929893.199470.2923 9904.46468.98979926.902464.2616
9937.902464.04239948.902458.60699970.901 457.4779981.901455.35839992.901454.9211
10004.11456.123410025.75460.766510036.52 469.28710101.15469.241910123.04469.9921
10145.33473.914310167.63480.809310190.64482.189210220.82480.590610234.42484.2036
10250.49487.024510263.09491.5574   10272497.403310288.57510.037910293.41512.6101
#Mann= 3 , 0 , 0
9783.455  0.0732       09783.455  0.0732       010293.41  0.0732       0
#XS Ineff= 2 , 0
       09968.938        10086.22       0
Bank Sta=9783.455,10293.41
Exp/Cntr=0.3,0.1

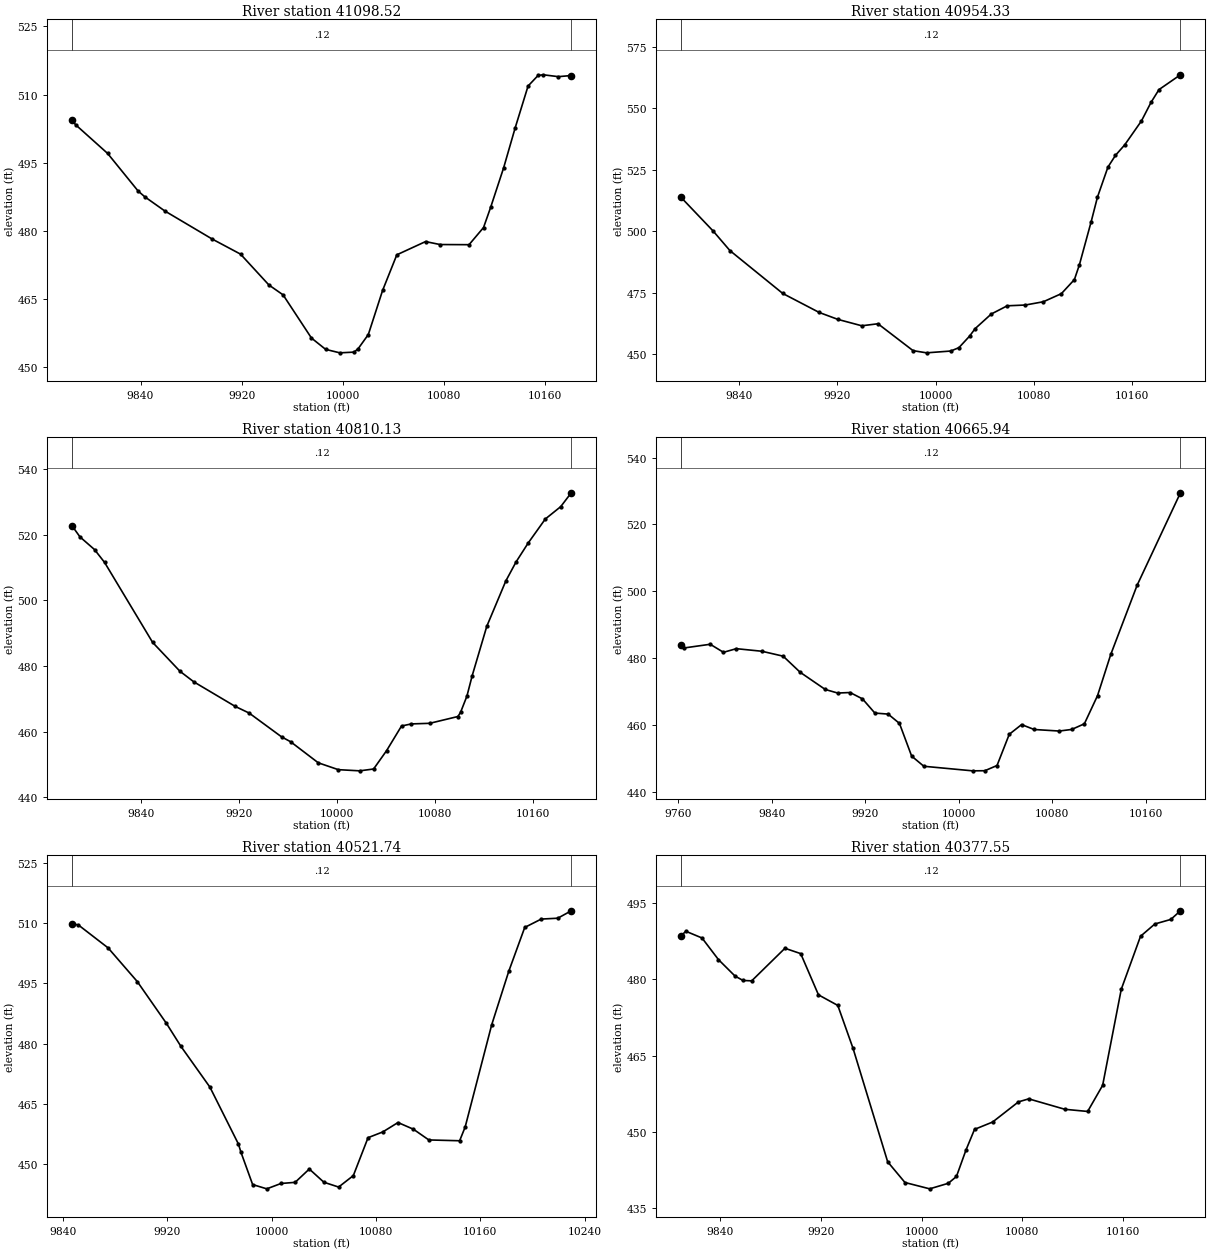
Type RM Length L Ch R = 1 ,41098.52,144.195400,144.195400,144.195400
XS GIS Cut Line= 6
821117.400068079730738.506775888821057.342103575730696.185788998
  821027.4649708730678.715071016820884.418844723730605.453844049
820821.126855977730569.952711532820776.455049806730540.562983467
#Sta/Elev= 30
9785.773504.36029788.797503.34149813.997497.05679838.074 488.7999843.371487.5177
9859.283484.38629896.659478.22519919.093474.90179941.527468.11339952.744465.9376
9975.178456.43939986.395453.94469997.613453.181510008.89453.340710012.19454.1215
10020.15457.205410031.42466.899310042.69474.750710065.41477.663210076.88477.0126
10099.81476.979610111.27480.753710116.86485.172710127.18493.910110136.19502.5979
10146.48511.891110154.38 514.21410158.45 514.36810170.42513.955210180.65514.2028
#Mann= 3 , 0 , 0
9785.773    0.12       09785.773    0.12       010180.65    0.12       0
#XS Ineff= 2 , 0
       0                               0
Bank Sta=9785.773,10180.65
Exp/Cntr=0.3,0.1

Type RM Length L Ch R = 1 ,40954.33,144.195400,144.195400,144.195400
XS GIS Cut Line= 6
 821160.89458662730674.346537297821086.101867726730592.517595495
821023.656960447730520.192765732820984.104563251730474.103880762
820911.411214851730395.875169099820887.866790657730372.744824562
#Sta/Elev= 30
9792.588513.74029818.798500.03049832.346492.14679875.436474.70689905.134466.9828
9920.436464.15459939.803461.57179953.014462.39119981.643451.45169992.649450.5712
10012.33451.3059   10019452.685910027.67457.358310032.18 460.40110045.37466.3568
10058.36469.693810073.11 470.009 10087.8471.339110102.49474.633710113.11480.3556
10117.18486.370310126.77503.887510131.87513.835210140.42526.070510146.56 530.847
10154.07535.094710167.77 544.86910175.51552.360210182.04557.587510199.53563.6141
#Mann= 3 , 0 , 0
9792.588    0.12       09792.588    0.12       010199.53    0.12       0
#XS Ineff= 2 , 0
       0                               0
Bank Sta=9792.588,10199.53
Exp/Cntr=0.3,0.1

Type RM Length L Ch R = 1 ,40810.13,144.195400,144.195400,144.195400
XS GIS Cut Line= 6
821249.387961947730630.548907539821203.550658795730554.815284312
821124.486890817730404.651418813821092.407721989 730348.60047149
821057.284519225730294.904768272821044.378500111730278.177313628
#Sta/Elev= 30
9783.281522.71129789.869519.28959801.743515.43739809.965 511.5239849.226487.1745
9871.605478.36889882.912475.15579916.814467.66549928.114 465.6589954.587458.4171
9962.016456.92229984.617450.5063   10001448.419510018.52448.061810029.83448.6228
10040.43454.200210052.65461.711710060.63462.348910075.69462.534510098.73464.6038
10100.89465.858510106.11470.814510110.41477.029210122.36492.087510137.91505.8879
10146.26511.667810156.18517.436510170.16524.741610182.78528.5192 10191.4532.7368
#Mann= 3 , 0 , 0
9783.281    0.12       09783.281    0.12       0 10191.4    0.12       0
#XS Ineff= 2 , 0
       0                               0
Bank Sta=9783.281,10191.4
Exp/Cntr=0.3,0.1

Type RM Length L Ch R = 1 ,40665.94,144.195400,144.195400,144.195400
XS GIS Cut Line= 6
  821362.7052687730606.957826863821315.603517263730506.924150951
821293.603265449730444.303264547 821262.22457687730338.497083234
821241.977292872 730286.22370479 821201.72874737730213.107181045
#Sta/Elev= 30
9762.655483.85989764.873483.02369787.527484.14239798.855481.73659809.878482.8234
9831.717 482.0529849.904480.57629864.476475.75299885.934470.60869896.533 469.546
9907.132469.70169917.731467.79829928.331463.55269939.668463.24519949.358460.4559
9959.774450.6714 9970.19447.631710011.88446.262710022.33446.296910032.78447.8568
10043.24457.200610053.78460.102610064.51458.635610085.95458.173310096.68458.6529
10107.47 460.34410118.75468.795210130.02481.084510152.58501.815310189.62529.4791
#Mann= 3 , 0 , 0
9762.655    0.12       09762.655    0.12       010189.62    0.12       0
#XS Ineff= 2 , 0
       0                               0
Bank Sta=9762.655,10189.62
Exp/Cntr=0.3,0.1

Type RM Length L Ch R = 1 ,40521.74,144.195400,144.195400,144.195400
XS GIS Cut Line= 6
821482.610222624730489.304008965 821431.60400819730388.906453315
821403.455592884730322.625826394 821377.27686625730272.656989906
821341.565995441730215.960304901821295.269295141730157.051451389
#Sta/Elev= 30
9846.792509.84899851.704509.54289874.527503.82789896.959495.42229919.233485.0444
 9930.37479.31269952.643469.13959974.535454.95039976.345453.01199985.397444.8843
9996.259443.820610007.11445.152110017.98445.439410028.86448.755210040.05445.4621
10051.34444.265410062.63 447.11710073.92456.561310085.21457.9917 10096.9 460.334
10108.72458.666210120.54455.997710144.17455.795810148.41459.218110168.75484.6653
10181.82497.9704 10194.1508.926610206.77511.005710219.44511.2224 10229.8513.0727
#Mann= 3 , 0 , 0
9846.792    0.12       09846.792    0.12       0 10229.8    0.12       0
#XS Ineff= 2 , 0
       0                               0
Bank Sta=9846.792,10229.8
Exp/Cntr=0.3,0.1

Type RM Length L Ch R = 1 ,40377.55,144.195400,144.195400,144.195400
XS GIS Cut Line= 6
821646.679893594730397.917610297821579.532084831730319.203201487
821503.343147596730237.809395614821437.078906949730173.642220517
821384.578635575730127.046635017821368.924200963730114.957625806
#Sta/Elev= 30
9808.763488.59969812.516489.48799825.378488.16289838.453483.90859851.676480.6584
9858.031479.7987  9864.9479.72389891.347486.1373 9903.88485.0838 9918.02476.9657
9933.392474.8846 9945.54466.41539973.059 444.1039986.819440.0254 10006.5 438.779
10021.29439.871210027.78441.213510035.35446.417910042.15450.483210056.53451.9285
10077.11455.902110085.28456.492710114.03454.437910132.13454.012910144.06 459.153
10158.87 478.06210174.19488.497710185.61490.921510198.28491.813810205.95493.5182
#Mann= 3 , 0 , 0
9808.763    0.12       09808.763    0.12       010205.95    0.12       0
#XS Ineff= 2 , 0
       0                10130.09       0
Bank Sta=9808.763,10205.95
Exp/Cntr=0.3,0.1

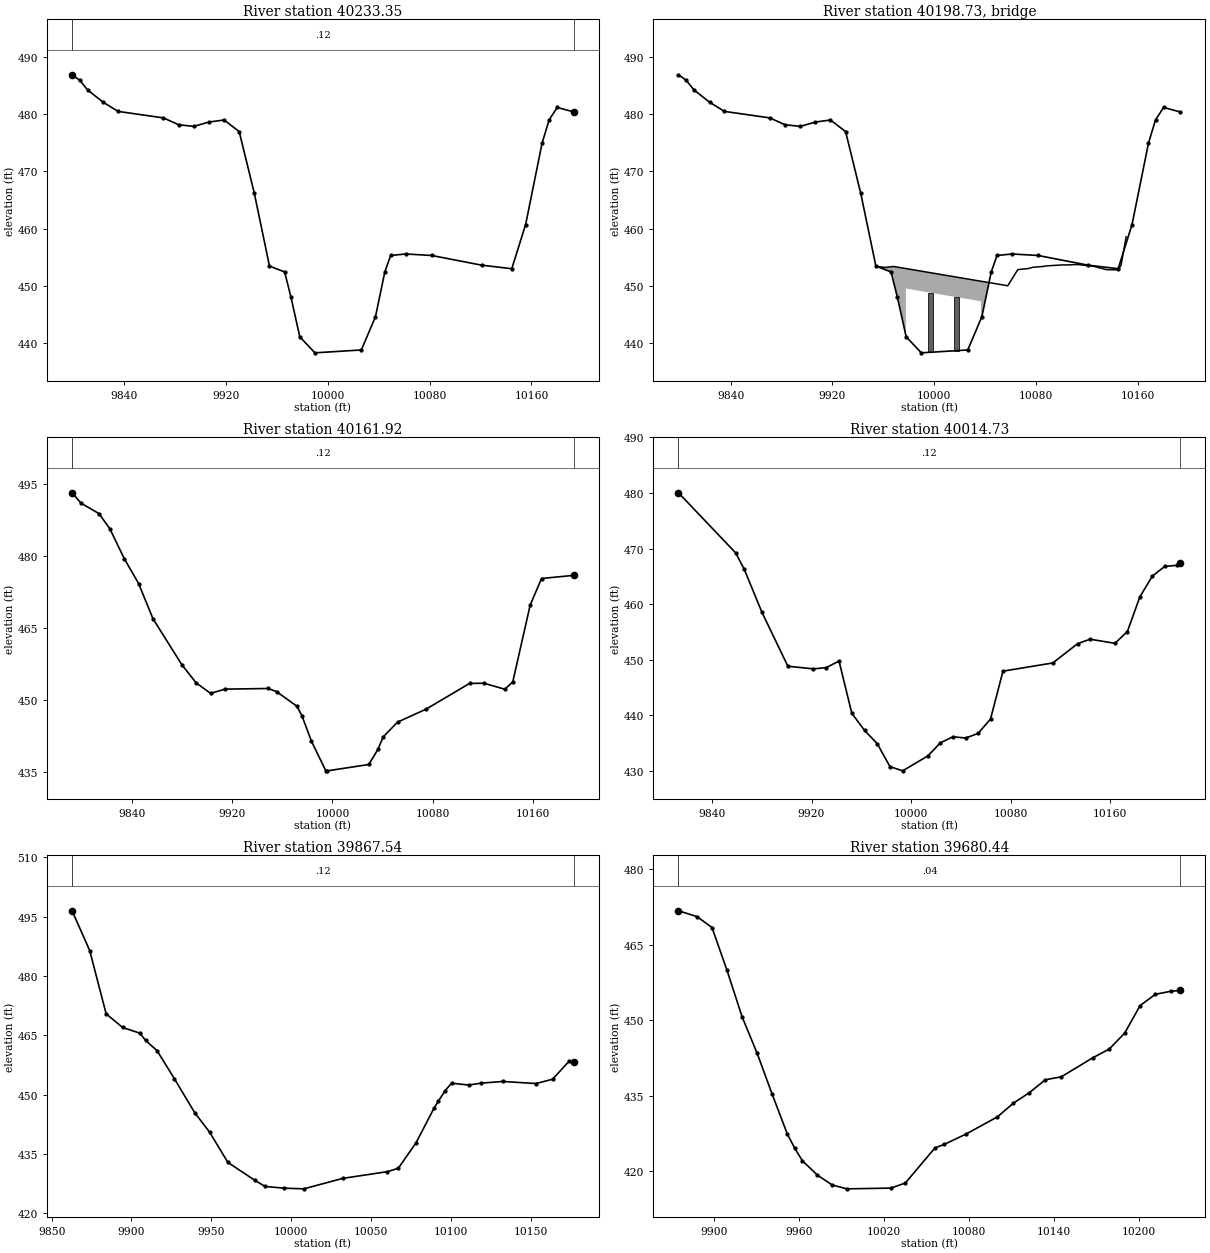
Type RM Length L Ch R = 1 ,40233.35,71.427100,71.427100,71.427100
XS GIS Cut Line= 2
821795.343273287730268.248908789821463.981560777730054.424239743
#Sta/Elev= 30
9798.979486.89329804.971485.94329811.289 484.2179823.415482.09969835.092480.4922
9870.795479.35579882.697478.15799894.598477.86899906.499478.62729918.401478.9907
9930.302476.96559942.203466.17849954.104453.45139966.006452.42669970.961448.0493
9977.907441.09139989.808438.284410026.29438.788610037.41444.609210044.73452.4151
10049.31455.307710061.22455.566410081.62455.302510120.72453.614310144.52452.9932
10155.39460.713910168.33474.944510173.84479.004110180.23481.182410193.34480.3933
#Mann= 3 , 0 , 0
9798.979    0.12       09798.979    0.12       010193.34    0.12       0
#XS Ineff= 2 , 0
       0 9965.13        10048.69       0
Bank Sta=9798.979,10193.34
Exp/Cntr=0.3,0.1

Type RM Length L Ch R = 3 ,40198.73,,,
BEGIN DESCRIPTION:
END DESCRIPTION:
Bridge Culvert--1,0,-1,-1, 0
Deck Dist Width WeirC Skew NumUp NumDn MinLoCord MaxHiCord MaxSubmerge Is_Ogee
24.213550,23.000000,2.6,0, 23, 23, , , 0.95, 0, 0,0,,
 9956.66 9961.13 9968.00 9977.68 9977.6810036.6810036.6810057.7510065.5010066.27
10073.5810077.4710085.1910089.0310100.5910105.1210112.1510123.7110125.0510135.28
10144.9710146.8410150.78
  453.35  453.21  453.38  453.02  453.02  450.80  450.80  450.01  452.79  452.85
  453.01  453.24  453.38  453.50  453.65  453.65  453.73  453.46  453.42  452.83
  452.79  453.71  458.57
 -546.65 -546.79 -546.62 -546.98  449.52  447.30 -549.20 -549.99 -547.21 -547.15
 -546.99 -546.76 -546.62 -546.50 -546.35 -546.35 -546.27 -546.54 -546.58 -547.17
 -547.21 -546.29 -541.43
 9956.66 9961.13 9968.00 9985.99 9985.9910044.9910044.9910057.7510065.5010066.27
10073.5810077.4710085.1910089.0310100.5910105.1210112.1510123.7110125.0510135.28
10144.9710146.8410150.78
  453.35  453.21  453.38  452.70  452.70  450.49  450.49  450.01  452.79  452.85
  453.01  453.24  453.38  453.50  453.65  453.65  453.73  453.46  453.42  452.83
  452.79  453.71  458.57
 -546.65 -546.79 -546.62 -547.30  449.20  446.99 -549.51 -549.99 -547.21 -547.15
 -546.99 -546.76 -546.62 -546.50 -546.35 -546.35 -546.27 -546.54 -546.58 -547.17
 -547.21 -546.29 -541.43
Pier Skew, UpSta & Num, DnSta & Num=  ,9996.68, 2 ,10004.99, 2 , 0 , 0 , 0 ,,
    4.00    4.00
 -547.70  452.30
    4.00    4.00
 -548.01  451.99
Pier Skew, UpSta & Num, DnSta & Num=  ,10017.68, 2 ,10025.99, 2 , 0 , 0 , 0 ,,
    4.00    4.00
 -548.49  451.51
    4.00    4.00
 -548.80  451.20
BR Coef=-1 , 0 , 0 ,, 0 ,,,0.8,0,1,0,
WSPro=,,,, 1 ,,,, 0 ,,,, 0 ,,,,-1 ,-1 ,-1 , 0 , 0 , 0 , 0 , 0
BC Design=,, 0 ,, 0 ,,,,,,

Type RM Length L Ch R = 1 ,40161.92,147.191200,147.191200,147.191200
XS GIS Cut Line= 2
821851.238801783730205.613611994821502.496433096730007.746290243
#Sta/Elev= 30
9791.979493.13579799.152490.97569813.487488.80459822.147485.65319833.645479.4593
9845.142474.2576 9856.64466.93039879.635457.39999891.132453.60589902.629 451.419
9914.127452.30659948.619452.43629955.337451.79139971.614448.75089975.602446.7824
9983.112441.55599994.609435.37169995.866435.3135 10029.1 436.63510036.39 439.809
 10040.6442.4019 10052.1445.449110075.09448.177110109.58453.496610121.08453.5281
10137.72452.284710144.08453.806810157.98469.763310167.07475.309210192.94475.9705
#Mann= 3 , 0 , 0
9791.979    0.12       09791.979    0.12       010192.94    0.12       0
#XS Ineff= 2 , 0
       09967.211        10063.54       0
Bank Sta=9791.979,10192.94
Exp/Cntr=0.3,0.1

Type RM Length L Ch R = 1 ,40014.73,147.191200,147.191200,147.191200
XS GIS Cut Line= 6
 821918.12675476730023.038267079 821844.28991222729996.820056305
821780.937403316729981.723509335821701.032053905729967.021821594
821651.101935002 729964.10721764821522.440600216729963.417330566
#Sta/Elev= 30
9813.018480.04859859.035469.22299865.737466.35889880.133458.53749900.981448.8327
9921.541448.36439931.821 448.5859942.101449.76799952.381440.37069962.619437.2871
9972.828434.90329983.037 430.7799993.246430.013410013.54432.701610023.67435.0708
 10033.8436.150210043.87435.911210053.88436.7452 10063.9439.336710073.92447.9511
10113.94449.423210133.94452.898310143.94453.700410163.94452.958510173.94455.0855
10183.94461.294910193.94465.041410203.94466.797910213.94466.9978 10216.5467.4523
#Mann= 3 , 0 , 0
9813.018    0.12       09813.018    0.12       0 10216.5    0.12       0
#XS Ineff= 2 , 0
       0                               0
Bank Sta=9813.018,10216.5
Exp/Cntr=0.3,0.1

Type RM Length L Ch R = 1 ,39867.54,187.105600,187.105600,187.105600
XS GIS Cut Line= 6
821815.722782033729781.986307464821785.478712656729789.425122374
821743.046130961729806.518590299821641.081039378729870.801112656
821608.643510181729886.894740392821531.971533168729911.198113445
#Sta/Elev= 30
9862.794496.46929873.837 486.4249884.135470.43529894.456466.98529905.237465.5495
9908.859463.70689916.018461.12349926.798454.09189939.686445.39669948.891440.5639
9960.331432.91779977.215428.3675 9983.73426.80859995.802426.379510007.97426.2131
10032.31428.855710060.33430.557410067.11431.418910078.28 437.88310089.44446.5638
10092.27448.425410096.54451.043710100.44452.909110111.17452.443610118.97452.9189
10132.49453.3432 10153.3452.8175 10163.7453.898610174.02458.4283 10177.1 458.347
#Mann= 3 , 0 , 0
9862.794    0.12       09862.794    0.12       0 10177.1    0.12       0
#XS Ineff= 2 , 0
       0                               0
Bank Sta=9862.794,10177.1
Exp/Cntr=0.3,0.1

Type RM Length L Ch R = 1 ,39680.44,254.467900,254.467900,254.467900
XS GIS Cut Line= 6
 821737.61393043729628.165469609821639.072537338729662.525215672
821562.564312718729683.398620036 821536.59868854729694.940912773
821451.956992188729739.111625221821408.743397936729757.033277276
#Sta/Elev= 30
9875.068471.79269888.212470.6299 9898.75468.46099909.379 459.9339920.008450.7193
9930.637443.47119941.267435.33349951.896427.45619957.253424.58339962.525422.1476
9973.154419.28449983.664417.30759994.001416.552610024.98416.696410035.26 417.704
10056.23 424.69810062.74425.379810078.02427.416210100.29 430.84910111.57433.5686
10122.85435.657710134.13438.214810145.41438.811610167.97442.638710179.25444.3137
10190.22447.500410201.04452.952710211.87455.202910222.69455.799510229.47455.9722
#Mann= 3 , 0 , 0
9875.068    0.04       09875.068    0.04       010229.47    0.04       0
#XS Ineff= 2 , 0
       0                               0
Bank Sta=9875.068,10229.47
Exp/Cntr=0.3,0.1