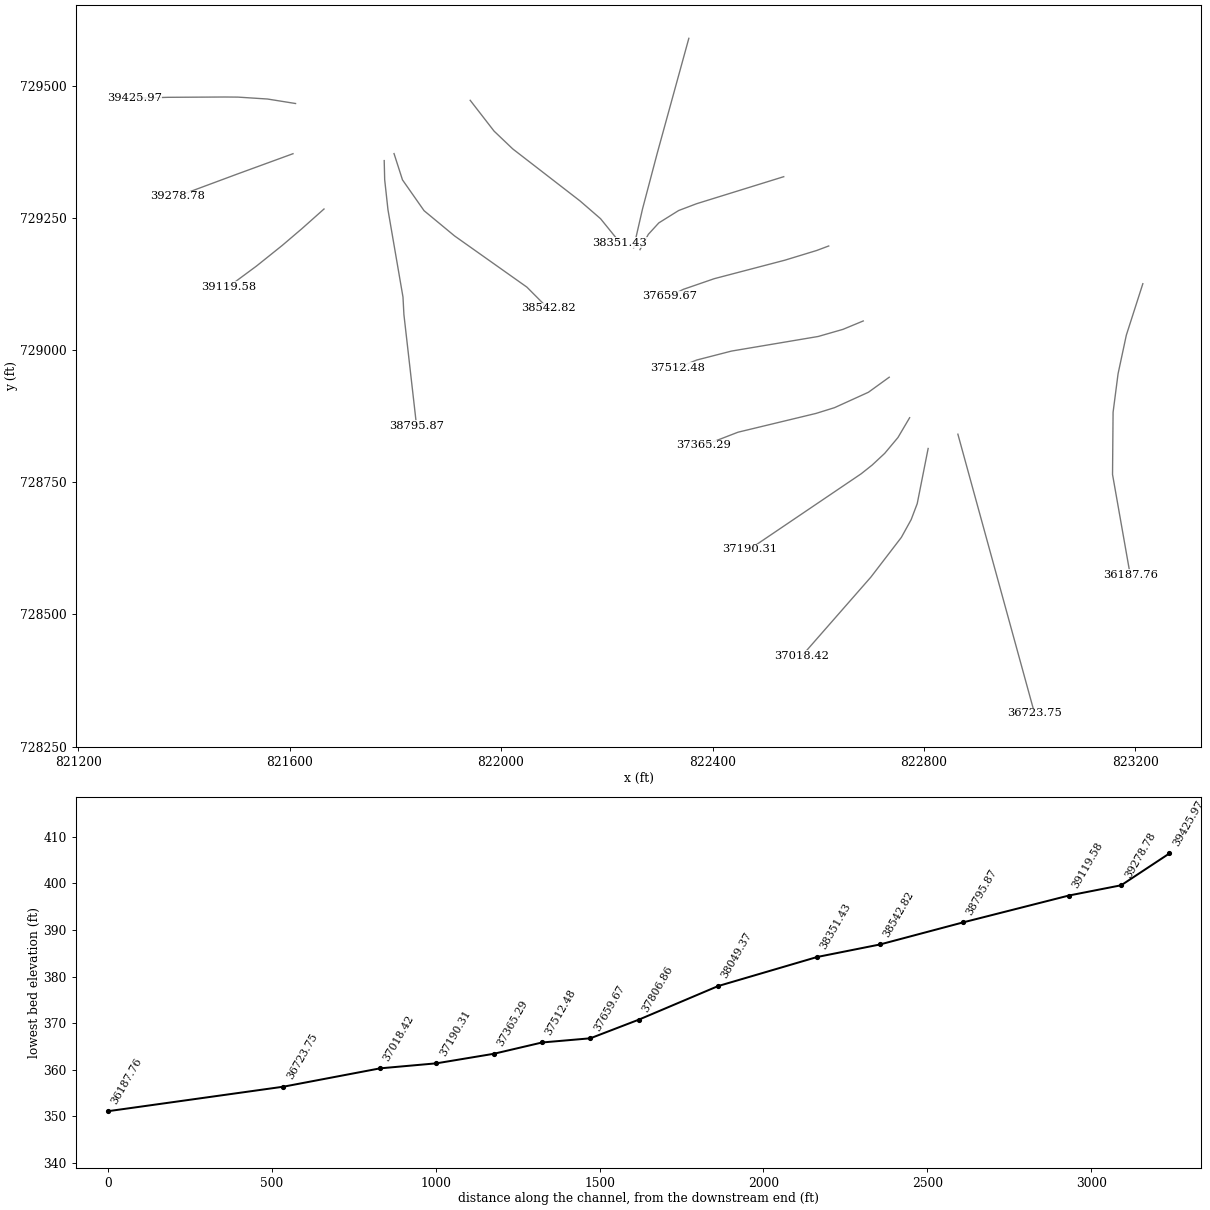
HEC-RAS study 7690_ras.prj: 7690

--- 7690_ras.g01 (geometry) --- (continued)

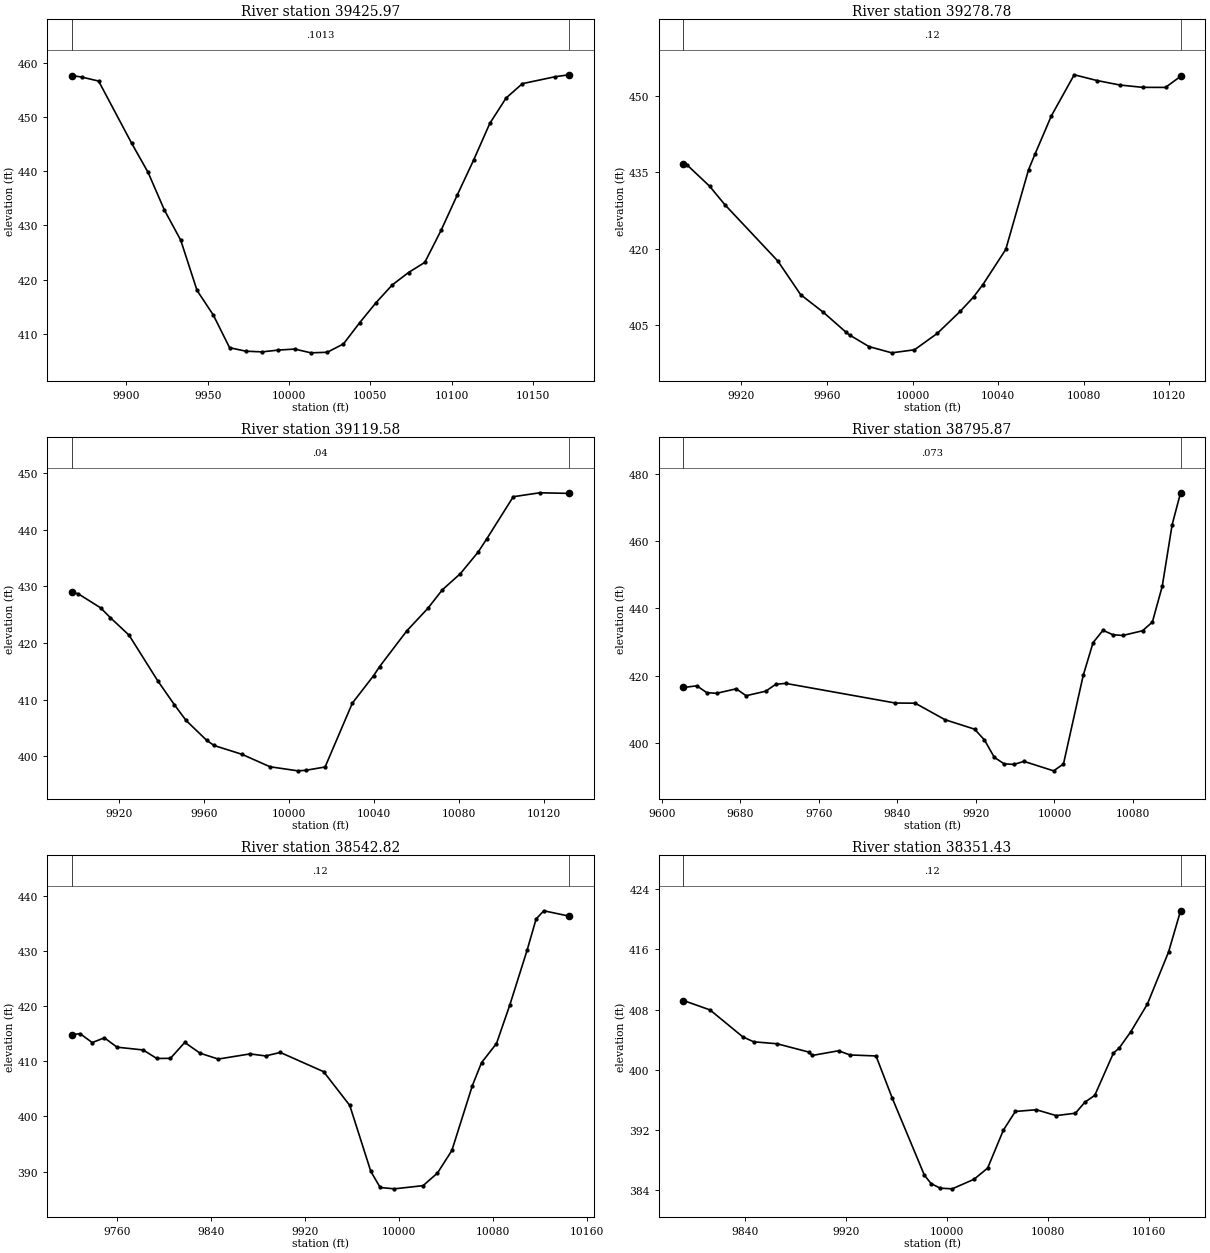
Type RM Length L Ch R = 1 ,39425.97,147.191200,147.191200,147.191200
XS GIS Cut Line= 6
821611.257185376729466.567614524821558.296373788729475.060105068
821502.347335382729478.677282432821477.472150952729478.876895761
821370.344295416729478.302099737821306.399062318729476.436776794
#Sta/Elev= 30
9866.421457.67929872.758457.37459882.886456.65369903.141445.20379913.269439.8111
9923.361432.82359933.382427.26779943.403417.99869953.424413.44069963.445407.4075
9973.466406.76429983.472406.63929993.472406.972810003.47407.156810013.47406.4606
10023.47406.564110033.47 408.11110043.47412.038310053.47415.714610063.47419.0048
10073.47421.293510083.47423.163510093.47429.066810103.47435.626510113.48442.0419
10123.48448.847610133.48453.520210143.49456.1766 10163.5457.4462 10172.1457.8135
#Mann= 3 , 0 , 0
9866.421  0.1013       09866.421  0.1013       0 10172.1  0.1013       0
#XS Ineff= 2 , 0
       0                               0
Bank Sta=9866.421,10172.1
Exp/Cntr=0.3,0.1

Type RM Length L Ch R = 1 ,39278.78,159.198600,159.198600,159.198600
XS GIS Cut Line= 4
821606.436639973729371.625603912821506.768628029729335.238128829
821504.882859593729334.571887658821388.402369643729291.281767078
#Sta/Elev= 26
9892.897436.65719894.427436.48379905.072432.27239912.217428.64869937.009417.5939
9947.655411.0173  9958.3  407.559968.946 403.6259970.535403.10799979.592400.8424
9990.237399.614110000.88400.212410011.54403.425310022.21407.724410028.48410.5528
10032.88413.000410043.55 419.87210054.22435.518310057.18438.509710064.88446.0558
10075.55454.089710086.22452.963110096.89 452.08310107.56451.625810118.23451.6151
10125.26453.7792
#Mann= 3 , 0 , 0
9892.897    0.12       09892.897    0.12       010125.26    0.12       0
#XS Ineff= 2 , 0
       0                               0
Bank Sta=9892.897,10125.26
Exp/Cntr=0.3,0.1

Type RM Length L Ch R = 1 ,39119.58,323.708900,323.708900,323.708900
XS GIS Cut Line= 6
821665.091593277729267.037354804821623.465053414729229.969522942
821586.140897616729198.169128768821584.579475893729196.919343305
821537.342044419729159.077293182821483.970840547729119.656040965
#Sta/Elev= 27
9897.925429.01889900.989428.68179911.438426.21589916.026424.47889924.828421.3797
9938.218413.3671  9946.1409.11299951.609406.32179961.327402.79869964.785401.8928
9977.922400.3293 9991.06398.134110004.16397.412810007.77397.502510016.97398.0922
10029.79409.377410039.76  414.22 10042.6415.830510055.41422.159410065.22426.0993
10072.09429.397410080.57432.255610088.92436.0735   10093438.417910105.43445.8465
10117.86446.542810131.58446.4329
#Mann= 3 , 0 , 0
9897.925    0.04       09897.925    0.04       010131.58    0.04       0
#XS Ineff= 2 , 0
       0                               0
Bank Sta=9897.925,10131.58
Exp/Cntr=0.3,0.1

Type RM Length L Ch R = 1 ,38795.87,253.048400,253.048400,253.048400
XS GIS Cut Line= 6
821778.968962088729358.599346084821779.862771062729322.480025282
821786.087420355729265.574501226821814.484985655729100.491249692
821816.254665825729067.253950821821840.244128669 728856.47247989
#Sta/Elev= 30
9622.135416.43849635.749416.93629645.755414.90699655.761414.70059675.867416.0412
9685.926413.98379706.045 415.347 9716.11417.39399726.257417.65519837.873411.8096
9858.166411.76099888.534406.84539918.588404.03519928.653400.83559938.717395.6522
9948.782393.69189958.846393.53619968.911394.43979999.104391.621710009.17393.6476
 10029.3420.036410039.36429.800310049.43433.453610059.49432.147510069.56431.9221
10089.69433.322410099.75435.914910109.81 446.57410119.88464.890710128.46474.4011
#Mann= 3 , 0 , 0
9622.135   0.073       09622.135   0.073       010128.46   0.073       0
#XS Ineff= 2 , 0
       0                               0
Bank Sta=9622.135,10128.46
Exp/Cntr=0.3,0.1

Type RM Length L Ch R = 1 ,38542.82,191.387500,191.387500,191.387500
XS GIS Cut Line= 6
821797.557320632729371.829113743821813.549829948729322.109099186
821854.355387604729263.840546056821911.983184028729216.145495389
822048.914615764729119.222105805822088.828330668729079.099605013
#Sta/Elev= 30
9721.376414.77429728.325414.99939738.712413.3769  9749.1414.23229759.827412.5433
9782.047412.03829793.693410.49529805.339410.5205 9817.49413.39839830.554411.4494
9846.005410.38899873.075411.32269886.358410.95499898.836411.58869935.706408.1072
9957.966401.99739975.907390.03889983.883387.12679995.928386.883710020.38387.4611
10032.64389.7435 10044.9393.830210062.35 405.58310070.16 409.74310082.88 413.194
10094.14420.126110108.99430.132510116.61435.752910123.16437.245810144.53436.2864
#Mann= 3 , 0 , 0
9721.376    0.12       09721.376    0.12       010144.53    0.12       0
#XS Ineff= 2 , 0
       0                               0
Bank Sta=9721.376,10144.53
Exp/Cntr=0.3,0.1

Type RM Length L Ch R = 1 ,38351.43,302.064300,302.064300,302.064300
XS GIS Cut Line= 6
821941.648194777729472.621467157821986.822566108729414.312454094
822022.131573475729380.671274711822149.508427305729282.182324254
822188.179891281729248.699711988822224.737513517729203.643081397
#Sta/Elev= 30
9791.576409.20239812.552407.95489838.472 404.3789847.067403.72239865.469403.4646
9890.576402.36239893.466401.91179914.238402.53229923.174401.97589943.831401.8422
9956.771396.19659982.063386.01599987.405384.89089994.562 384.28410004.07384.1956
10021.34385.465310032.07 386.94310044.59392.005410053.99394.4704 10070.6394.6998
10086.26393.922410101.53394.2382   10109395.703610116.81396.608110131.56402.2173
10136.29402.921610145.41405.089610158.42408.7331 10175.2415.666910184.66421.1211
#Mann= 3 , 0 , 0
9791.576    0.12       09791.576    0.12       010184.66    0.12       0
#XS Ineff= 2 , 0
       09941.638        10126.06       0
Bank Sta=9791.576,10184.66
Exp/Cntr=0.3,0.1

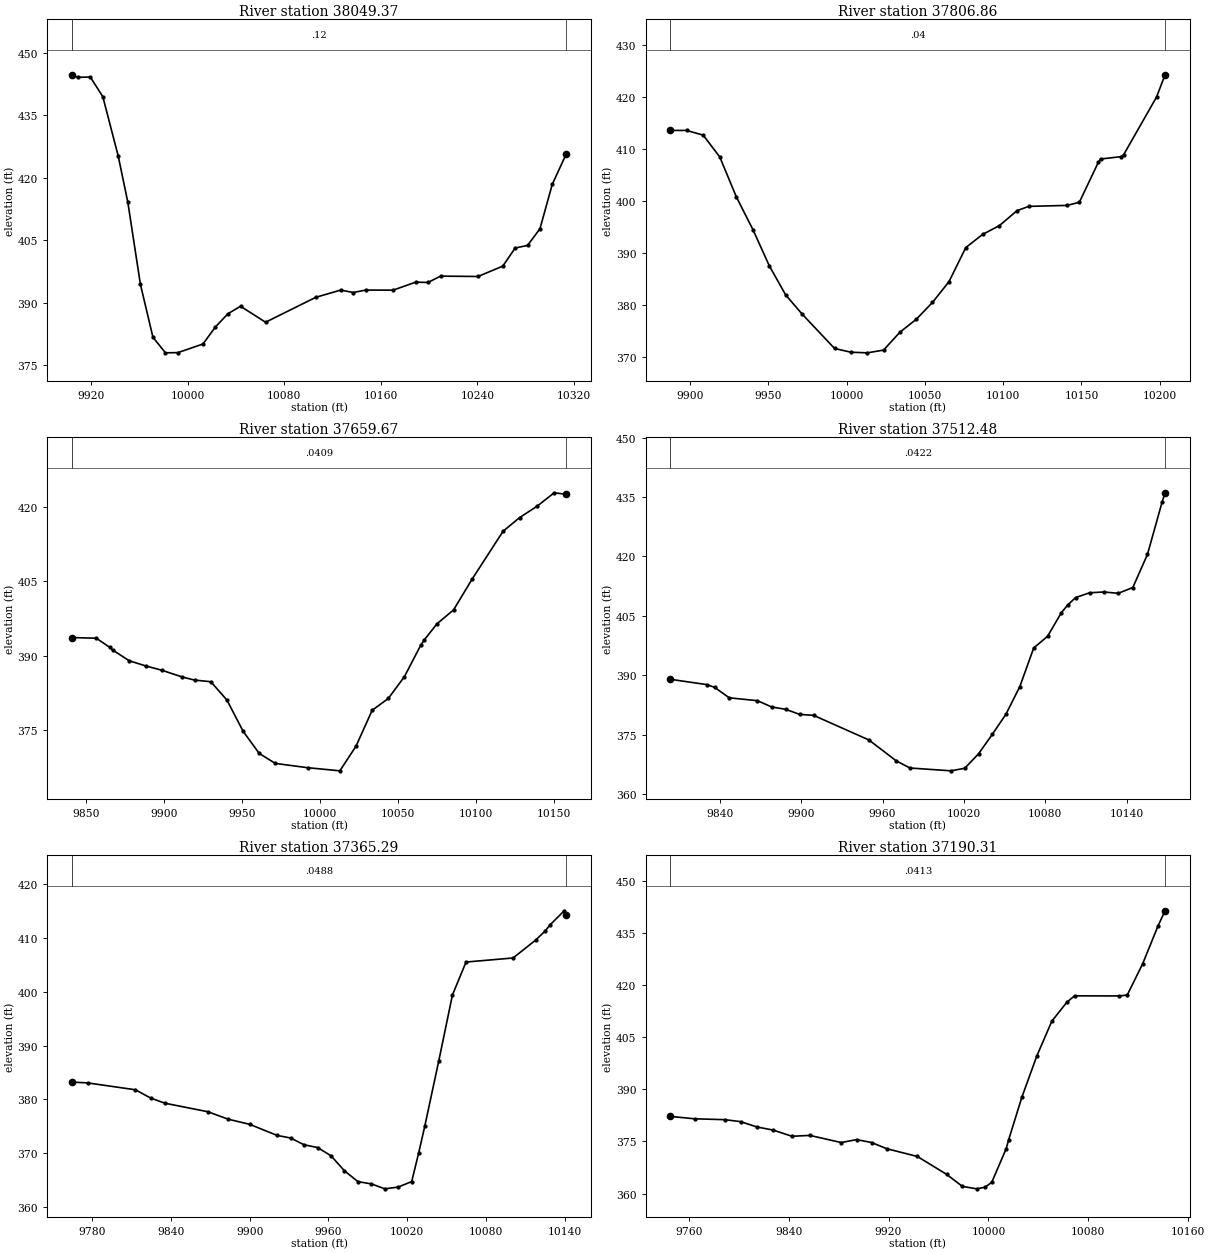
Type RM Length L Ch R = 1 ,38049.37,242.504100,242.504100,242.504100
XS GIS Cut Line= 4
822355.205951101729589.860262696822295.556011814 729372.96698407
822267.541220652729266.914071359822250.757008535729193.707230147
#Sta/Elev= 30
9903.849444.7182 9908.89444.10689919.261 444.1799929.633439.44929942.337425.2603
9950.375414.05569960.746394.42029971.118381.70749981.489377.9474 9991.86378.0032
 10012.6380.071510022.97384.195710033.35387.344610043.72389.135810064.46385.2964
10105.94391.266410126.69393.022810137.04 392.43410147.38393.014310170.13393.0055
10188.75394.912510199.09394.855710209.44396.368910240.45 396.28410260.97398.7688
10271.23 403.11410281.49403.747410291.75407.733910302.01418.448810313.59 425.732
#Mann= 3 , 0 , 0
9903.849    0.12       09903.849    0.12       010313.59    0.12       0
#XS Ineff= 2 , 0
       0                               0
Bank Sta=9903.849,10313.59
Exp/Cntr=0.3,0.1

Type RM Length L Ch R = 1 ,37806.86,147.191100,147.191100,147.191100
XS GIS Cut Line= 6
822534.719396562729328.144486614 822369.75855528729276.989394815
822335.912280354729264.133863644822298.408177519729240.728656494
822278.592921831729219.102432746822262.775042725729190.066055851
#Sta/Elev= 30
9887.569 413.5939897.867413.58889908.463 412.6859919.058408.47859929.654400.7632
9940.249394.45459950.692387.48059961.111381.8851 9971.53378.21549992.367371.5467
10002.78370.8275 10013.2370.709110023.62371.233910034.04374.679310044.45377.1618
10054.87  380.4310065.42384.444210076.12391.000310086.82393.529510097.57395.2382
10108.84398.1212 10116.3398.948410140.86399.135910148.63399.7444 10160.7407.4086
10162.19408.078910175.06408.529310176.84408.868910197.93420.036910203.34424.3204
#Mann= 3 , 0 , 0
9887.569    0.04       09887.569    0.04       010203.34    0.04       0
#XS Ineff= 2 , 0
       0                               0
Bank Sta=9887.569,10203.34
Exp/Cntr=0.3,0.1

Type RM Length L Ch R = 1 ,37659.67,147.191200,147.191200,147.191200
XS GIS Cut Line= 6
822619.782779062729197.074973107822597.027040708729188.566489171
822536.730973596729170.171677049822403.314656998729135.225570281
822344.810593035729115.052005167822318.197582512729101.890644286
#Sta/Elev= 30
9841.013393.62939856.795 393.4979865.307391.67489867.426391.07859877.881388.9455
9888.336 387.9149898.791387.0289  9911.8385.67159919.701385.04719930.135384.7135
9940.467381.00569950.799374.7215 9961.13 370.2379971.462368.21939992.126367.3562
 10012.8366.720910023.14371.695310033.49378.944310043.83 381.33510054.18385.7551
10064.52392.029210066.96393.195810075.06396.425310085.64399.217710097.63405.4857
10117.37415.099910127.95417.854210139.03420.129410150.12422.866110157.86422.5513
#Mann= 3 , 0 , 0
9841.013  0.0409       09841.013  0.0409       010157.86  0.0409       0
#XS Ineff= 2 , 0
       0                               0
Bank Sta=9841.013,10157.86
Exp/Cntr=0.3,0.1

Type RM Length L Ch R = 1 ,37512.48,147.191200,147.191200,147.191200
XS GIS Cut Line= 6
 822685.11928554729055.254874888822646.784517681729039.369455129
822599.916483995 729025.89474917822435.833952273728998.264564092
822370.171487024728981.348289429822332.962366224728966.400138196
#Sta/Elev= 30
9803.634388.93759830.422387.60949836.237386.90319846.987384.26759867.797383.5404
9878.202381.96479888.607381.35769898.911380.0754 9909.11379.84469949.863373.6364
9970.081368.3498 9980.19366.538410010.53365.820710020.66  366.4810030.79370.1307
10040.92 375.03510051.04380.162510061.18387.090410071.43 396.84110081.68399.8201
10091.93405.818410096.55407.732510102.28409.582510112.71410.805910123.14411.0009
10133.74410.667710144.52412.1324 10155.3420.489710166.07433.677510168.27436.0638
#Mann= 3 , 0 , 0
9803.634  0.0422       09803.634  0.0422       010168.27  0.0422       0
#XS Ineff= 2 , 0
       0                               0
Bank Sta=9803.634,10168.27
Exp/Cntr=0.3,0.1

Type RM Length L Ch R = 1 ,37365.29,174.985200,174.985200,174.985200
XS GIS Cut Line= 6
822734.268795629728948.825927066822694.954898285728920.409195521
822630.789546032728891.243385872822595.796426453728880.361858788
822448.214491786728844.813441041 822383.54493026728819.794471085
#Sta/Elev= 30
 9764.27383.22849776.344383.07949812.775381.80259824.539 380.2549835.329379.3034
9868.087 377.7199883.398376.34629899.933375.37689920.861373.31979931.125372.8394
9941.389371.57649951.654371.07339961.918369.53679972.182366.74349982.446364.7353
 9992.71364.310110002.95 363.39310013.19363.722810023.43364.753510028.68370.0022
10033.46375.1069 10044.1387.213310054.47399.408410064.84405.538210100.71406.2924
10117.84409.605810124.86 411.23410129.04412.482210139.67415.063510141.27 414.242
#Mann= 3 , 0 , 0
 9764.27  0.0488       0 9764.27  0.0488       010141.27  0.0488       0
#XS Ineff= 2 , 0
       0                               0
Bank Sta=9764.27,10141.27
Exp/Cntr=0.3,0.1

Type RM Length L Ch R = 1 ,37190.31,171.889800,171.889800,171.889800
XS GIS Cut Line= 6
822772.873550205728872.223347553822750.759250881728834.728595955
822725.674793052728804.761566906822702.043708957728782.728888583
822681.134156113 728766.11422146822470.455927373728623.629031432
#Sta/Elev= 30
9745.395382.17639764.796381.49019788.987381.23889801.674380.66579814.715 379.135
9827.756378.23549842.662376.46429857.045376.71629882.145374.65569894.457375.5079
 9906.48374.66589918.502 372.8989943.132370.64919966.592365.49169979.161362.0493
9990.637361.34189997.175361.802610002.66363.205110014.25372.907210016.25375.5071
10026.76387.667510038.79399.590910050.83 409.61110062.87415.0524   10069416.8687
 10104.9416.835610111.18417.105110123.51426.080410135.84436.994210141.44441.3398
#Mann= 3 , 0 , 0
9745.395  0.0413       09745.395  0.0413       010141.44  0.0413       0
#XS Ineff= 2 , 0
       0                               0
Bank Sta=9745.395,10141.44
Exp/Cntr=0.3,0.1

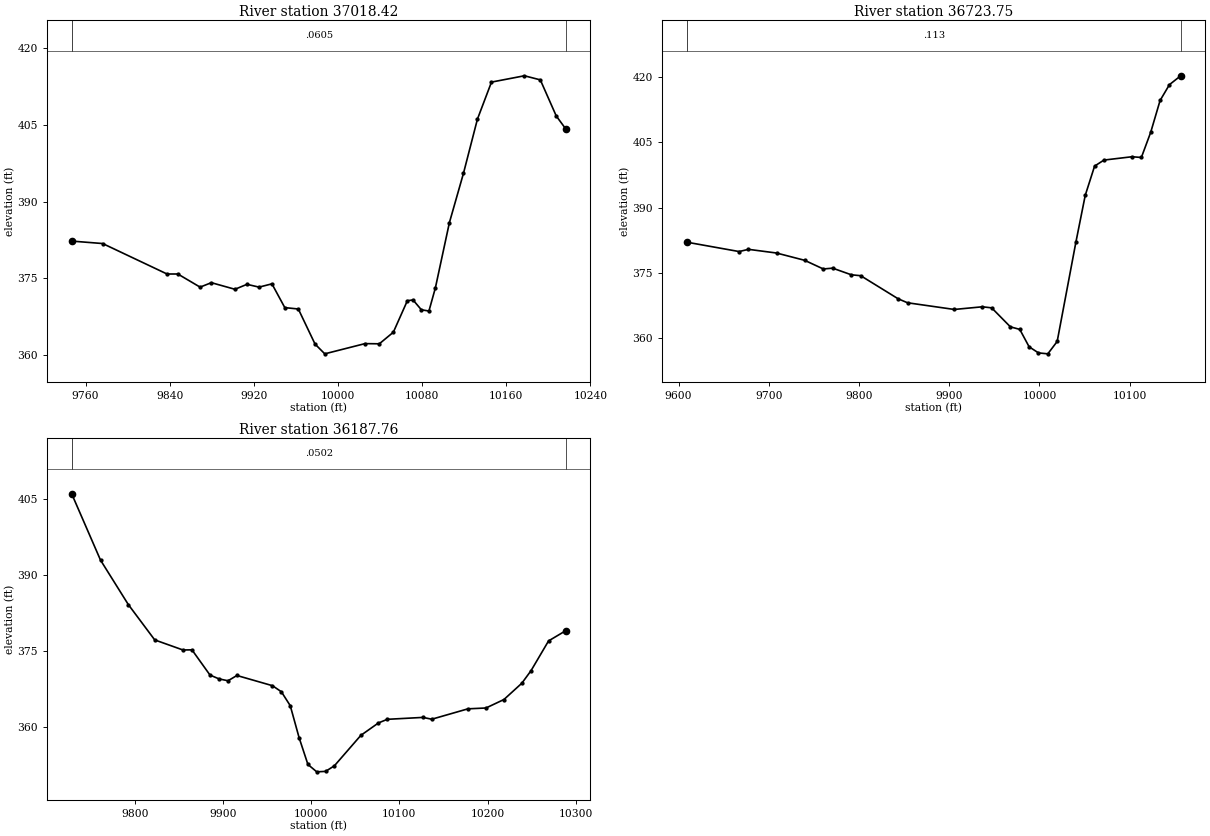
Type RM Length L Ch R = 1 ,37018.42,294.662900,294.662900,294.662900
XS GIS Cut Line= 6
822807.879695217728814.004986376822787.223223866 728709.67966041
 822775.77638993728679.475405728822757.308262462728645.985246696
 822699.62490545728570.795232326822569.191036051728421.834612972
#Sta/Elev= 30
9746.845 382.2769776.289381.79719837.492375.85089847.773375.84899868.941373.2856
9879.635374.15559902.074372.86639913.494373.83359924.994373.28729937.231373.9275
9949.467369.28769962.324369.01589978.233362.16589987.483360.262310025.73362.2575
10039.36362.221110052.67364.4828   10066 370.63310071.39370.782110079.33368.8613
10086.52368.621810092.65373.151510105.98385.888410119.31395.480910132.64406.1003
10145.97 413.31610177.27414.5504 10192.4413.7523 10207.6406.6874 10216.6 404.176
#Mann= 3 , 0 , 0
9746.845  0.0605       09746.845  0.0605       0 10216.6  0.0605       0
#XS Ineff= 2 , 0
       0                               0
Bank Sta=9746.845,10216.6
Exp/Cntr=0.3,0.1

Type RM Length L Ch R = 1 ,36723.75,535.991500,535.991500,535.991500
XS GIS Cut Line= 2
822864.131829969728841.092278053823009.185945482728312.950745809
#Sta/Elev= 30
9608.882382.03689667.051379.87289677.421380.38249708.532379.53459739.643377.8599
9760.384375.86169770.754376.05079791.495  374.529801.865374.30999843.346368.9967
9853.717368.08129905.568366.54129936.679367.15399947.049 366.909 9967.79362.5332
 9978.16361.95489988.531357.94229998.901356.539910009.27 356.32210019.64359.1696
10040.38382.029810050.75392.816610061.12399.548310071.49400.9338 10102.6 401.703
10112.97401.533410123.34407.347210133.71414.655110144.09418.301710156.58420.3436
#Mann= 3 , 0 , 0
9608.882   0.113       09608.882   0.113       010156.58   0.113       0
#XS Ineff= 2 , 0
       0                               0
Bank Sta=9608.882,10156.58
Exp/Cntr=0.3,0.1

Type RM Length L Ch R = 1 ,36187.76,271.356900,271.356900,271.356900
XS GIS Cut Line= 6
823214.010947544729125.718414694823182.756303387729028.331842678
823167.143743305728955.343659326823157.717008616728882.496675317
823156.679801861728764.795946061823190.005439898728575.642822142
#Sta/Elev= 30
9728.343406.08389761.036392.95469792.545384.1627 9822.53377.15739854.545375.1654
9864.771  375.199885.224370.2004 9895.45369.44279905.671  369.079915.755370.1155
9956.088368.09529966.172 366.8959976.255364.13589986.279357.80749996.282352.5061
10006.29351.042910016.29351.134310026.29352.235510056.31358.262510076.32360.7274
10086.32361.439510126.62361.816710136.83361.462310177.76363.513310198.23363.6812
10218.59365.355710238.89368.580810249.33371.065510269.24376.960410288.73 378.983
#Mann= 3 , 0 , 0
9728.343  0.0502       09728.343  0.0502       010288.73  0.0502       0
#XS Ineff= 2 , 0
       0                               0
Bank Sta=9728.343,10288.73
Exp/Cntr=0.3,0.1