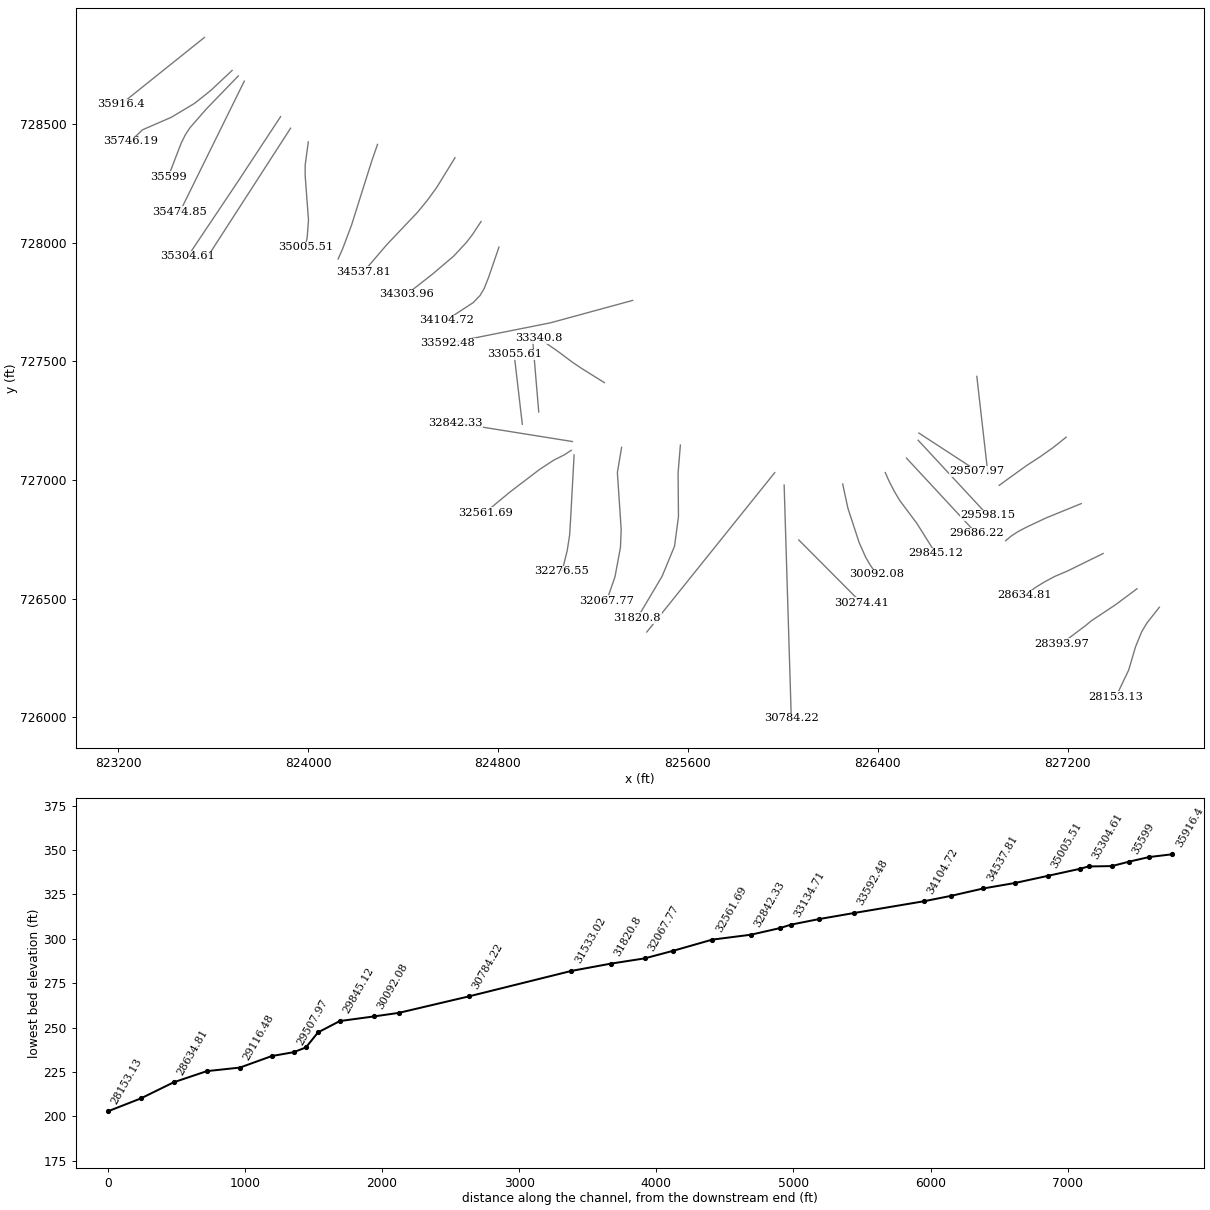
HEC-RAS study 7690_ras.prj: 7690

--- 7690_ras.g01 (geometry) --- (continued)

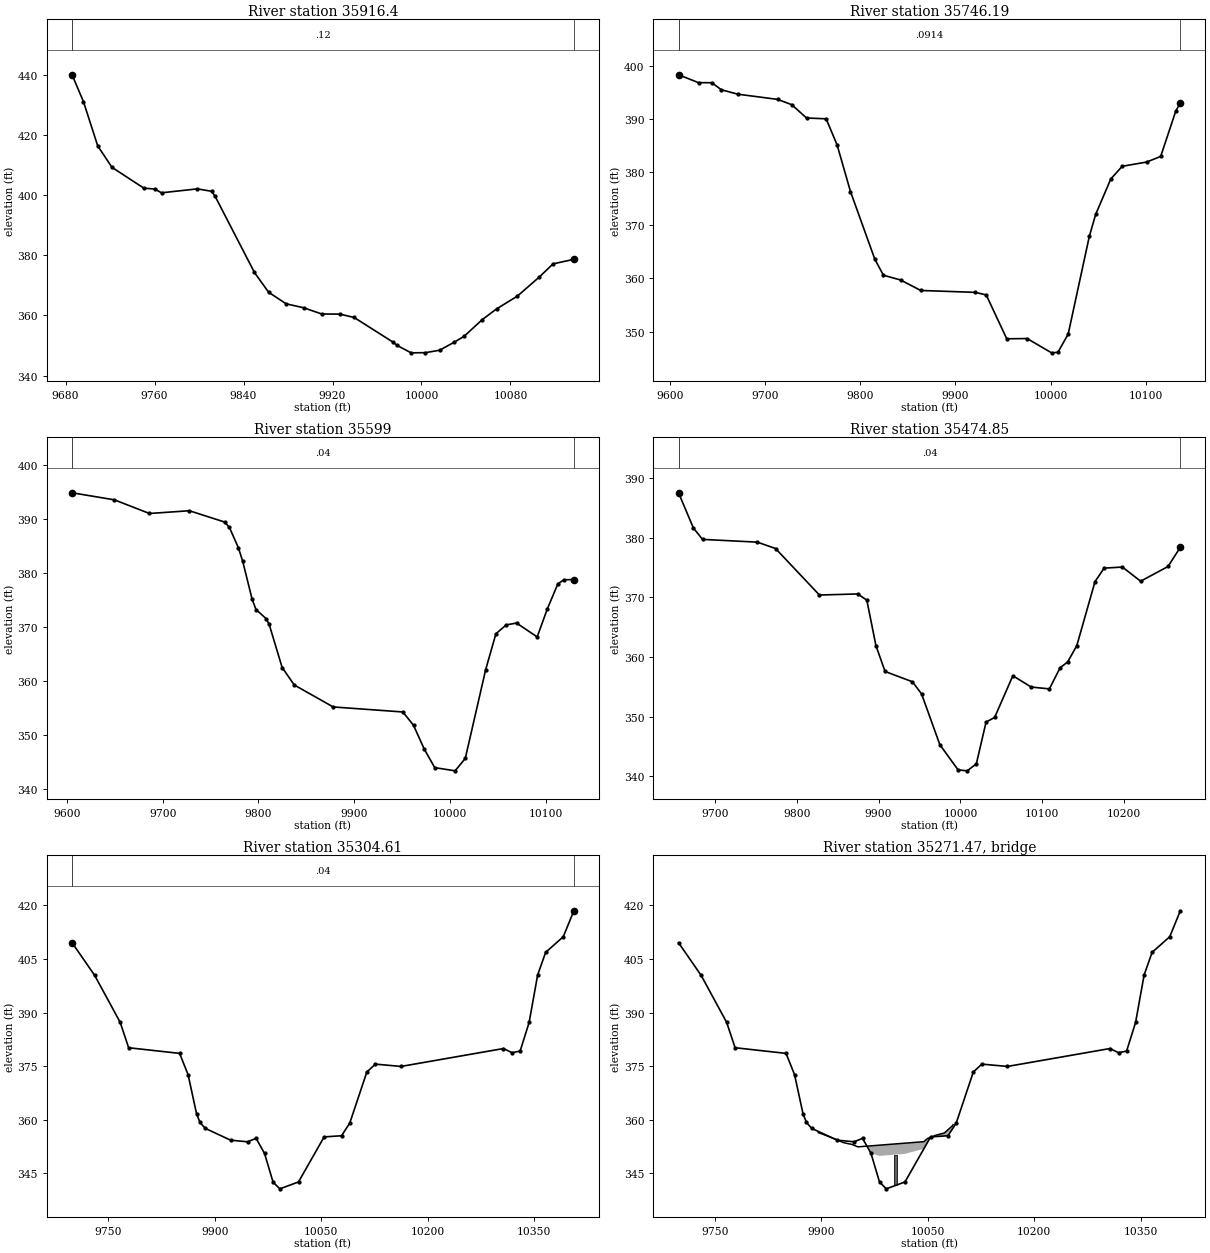
Type RM Length L Ch R = 1 , 35916.4,170.216700,170.216700,170.216700
XS GIS Cut Line= 2
823563.009356579728865.291094625823210.770257461728583.280841223
#Sta/Elev= 30
9685.797440.07849696.057431.12139708.867 416.4149721.677409.28139750.264402.3779
9760.108402.05079766.264400.81189798.538402.11749811.348401.30449814.265399.7639
9849.779374.30799862.589367.69839878.266363.88129894.266362.53149910.266360.4899
9926.639  360.44 9939.45359.32699974.267351.1599 9977.88350.0708 9990.69347.5619
 10003.5 347.61610016.31348.430710029.12 351.03510038.27353.045310054.74358.6434
10067.55 362.18410086.27366.442910105.98372.794910118.27377.161610137.02378.6844
#Mann= 3 , 0 , 0
9685.797    0.12       09685.797    0.12       010137.02    0.12       0
#XS Ineff= 2 , 0
       0                               0
Bank Sta=9685.797,10137.02
Exp/Cntr=0.3,0.1

Type RM Length L Ch R = 1 ,35746.19,147.191100,147.191100,147.191100
XS GIS Cut Line= 6
 823679.75321275728726.451830536823590.331164461728642.363536159
823521.475562326728587.518757677823423.751425188728529.018777962
823302.403717998728476.238905442823251.937471058728428.208611133
#Sta/Elev= 30
9608.895398.35959629.891396.87279643.917 396.8679653.803395.54689671.056394.7054
9712.977393.72729727.771392.7371 9743.49390.21749764.056390.06639775.591385.1439
9789.625376.36399815.194363.63529824.259360.60199842.362359.70369863.457357.7322
9920.816357.3761 9932.34356.8844 9953.91348.62959975.414348.6715   10001345.9818
 10007.7346.084910018.49349.512910040.72367.929610047.36372.0466 10063.3378.7395
 10075.3381.124710100.87381.915310115.72382.978710131.53391.494610136.37393.0841
#Mann= 3 , 0 , 0
9608.895  0.0914       09608.895  0.0914       010136.37  0.0914       0
#XS Ineff= 2 , 0
       0                               0
Bank Sta=9608.895,10136.37
Exp/Cntr=0.3,0.1

Type RM Length L Ch R = 1 ,   35599,124.148700,124.148700,124.148700
XS GIS Cut Line= 6
 823705.72930919 728703.05227885823569.385551932728562.099026767
823502.449180033728485.158253305823482.513084475728454.932208554
  823464.6707053728418.690909781823411.088412339 728279.44046882
#Sta/Elev= 30
 9605.35394.79989649.548393.49529686.117390.96869727.855391.47789764.614389.3881
9769.594 388.4099778.997384.63339783.507382.1506 9793.38375.0885 9797.42 373.204
9807.923371.52459811.114370.4839 9824.72362.47719837.419359.23959878.035 355.184
9950.775354.25489961.921351.78529973.067347.3965 9984.03343.9613 10005.3343.3659
10015.95345.667410037.25362.0951 10047.9368.715310058.66370.355710069.44 370.705
   10091368.134310101.78373.385610112.55377.929310118.84378.703210129.32378.7454
#Mann= 3 , 0 , 0
 9605.35    0.04       0 9605.35    0.04       010129.32    0.04       0
#XS Ineff= 2 , 0
       0                               0
Bank Sta=9605.35,10129.32
Exp/Cntr=0.3,0.1

Type RM Length L Ch R = 1 ,35474.85,170.233700,170.233700,170.233700
XS GIS Cut Line= 2
 823731.10776499728681.285023593823460.077209487728131.531248865
#Sta/Elev= 30
9655.593387.58129673.749 381.6669684.898379.75449751.794379.29219774.092 378.221
 9827.71370.41069874.435370.59459885.584369.55259896.734361.90719907.883357.5757
9941.331355.8428 9952.48353.79889974.778345.27899997.077341.048810008.23340.8893
10019.38342.065910031.24349.080710041.67349.849510063.97 356.85510086.27354.9638
10108.57354.6499 10121.7358.202210130.87 359.16810142.02361.892410164.32372.6639
10175.46374.924210197.76375.112110220.06372.729110253.51 375.20310268.53378.4327
#Mann= 3 , 0 , 0
9655.593    0.04       09655.593    0.04       010268.53    0.04       0
#XS Ineff= 2 , 0
       0                10067.18       0
Bank Sta=9655.593,10268.53
Exp/Cntr=0.3,0.1

Type RM Length L Ch R = 1 ,35304.61,65.252400,65.252400,65.252400
XS GIS Cut Line= 5
823884.046397586728531.594170726823723.154081866728287.039177905
823722.110711326728285.332899875823710.715442502728267.936780731
 823492.87658795727942.618765727
#Sta/Elev= 30
9698.721409.55579730.555400.41729766.465387.29369778.435380.16949850.256378.5847
9862.226372.61639874.196361.62279878.931359.29919886.166357.62739922.076354.3085
9946.017353.84729957.987354.81649969.903350.60639981.927342.57969991.456340.6856
10017.79342.612810053.89355.215910078.44355.5419   10090359.086610114.07 373.367
 10126.1 375.58210162.21374.933910306.62379.943810318.66378.777210330.06379.2289
10342.73387.247610354.76 400.53910366.01406.853510390.87411.234310405.77418.4896
#Mann= 3 , 0 , 0
9698.721    0.04       09698.721    0.04       010405.77    0.04       0
#XS Ineff= 2 , 0
       09959.452        10048.83       0
Bank Sta=9698.721,10405.77
Exp/Cntr=0.3,0.1

Type RM Length L Ch R = 3 ,35271.47,,,
BEGIN DESCRIPTION:
END DESCRIPTION:
Bridge Culvert--1,0,-1,-1, 0
Deck Dist Width WeirC Skew NumUp NumDn MinLoCord MaxHiCord MaxSubmerge Is_Ogee
24.126200,17.000000,2.6,0, 21, 21, , , 0.95, 0, 0,0,,
 9895.61 9902.13 9906.82 9918.70 9920.64 9930.59 9939.15 9942.47 9951.48 9960.86
 9960.8610044.3610047.8610047.8610049.4310050.1910061.3210068.6910073.2010085.08
10085.54
  356.42  355.95  355.59  354.69  354.55  353.65  353.26  353.16  352.43  352.58
  352.58  353.88  354.49  354.49  354.77  354.83  355.69  356.08  356.31  358.41
  358.63
 -643.58 -644.05 -644.41 -645.31 -645.45 -646.35 -646.74 -646.84 -647.57 -647.42
  349.58  350.88  351.49 -645.51 -645.23 -645.17 -644.31 -643.92 -643.69 -641.59
 -641.37
 9895.61 9902.13 9906.82 9918.70 9920.64 9930.59 9939.15 9942.47 9951.07 9951.07
 9951.4810038.0710038.0710044.3610049.4310050.1910061.3210068.6910073.2010085.08
10085.54
  356.42  355.95  355.59  354.69  354.55  353.65  353.26  353.16  352.47  352.47
  352.43  353.78  353.78  353.88  354.77  354.83  355.69  356.08  356.31  358.41
  358.63
 -643.58 -644.05 -644.41 -645.31 -645.45 -646.35 -646.74 -646.84 -647.53  349.47
  349.43  350.78 -646.22 -646.12 -645.23 -645.17 -644.31 -643.92 -643.69 -641.59
 -641.37
Pier Skew, UpSta & Num, DnSta & Num=  ,10004.36, 2 ,9994.57, 2 , 0 , 0 , 0 ,,
    3.00    3.00
 -646.74  353.26
    3.00    3.00
 -646.89  353.11
BR Coef=-1 , 0 , 0 ,, 0 ,,,0.8,0,1,0,
WSPro=,,,, 1 ,,,, 0 ,,,, 0 ,,,,-1 ,-1 ,-1 , 0 , 0 , 0 , 0 , 0
BC Design=,, 0 ,, 0 ,,,,,,

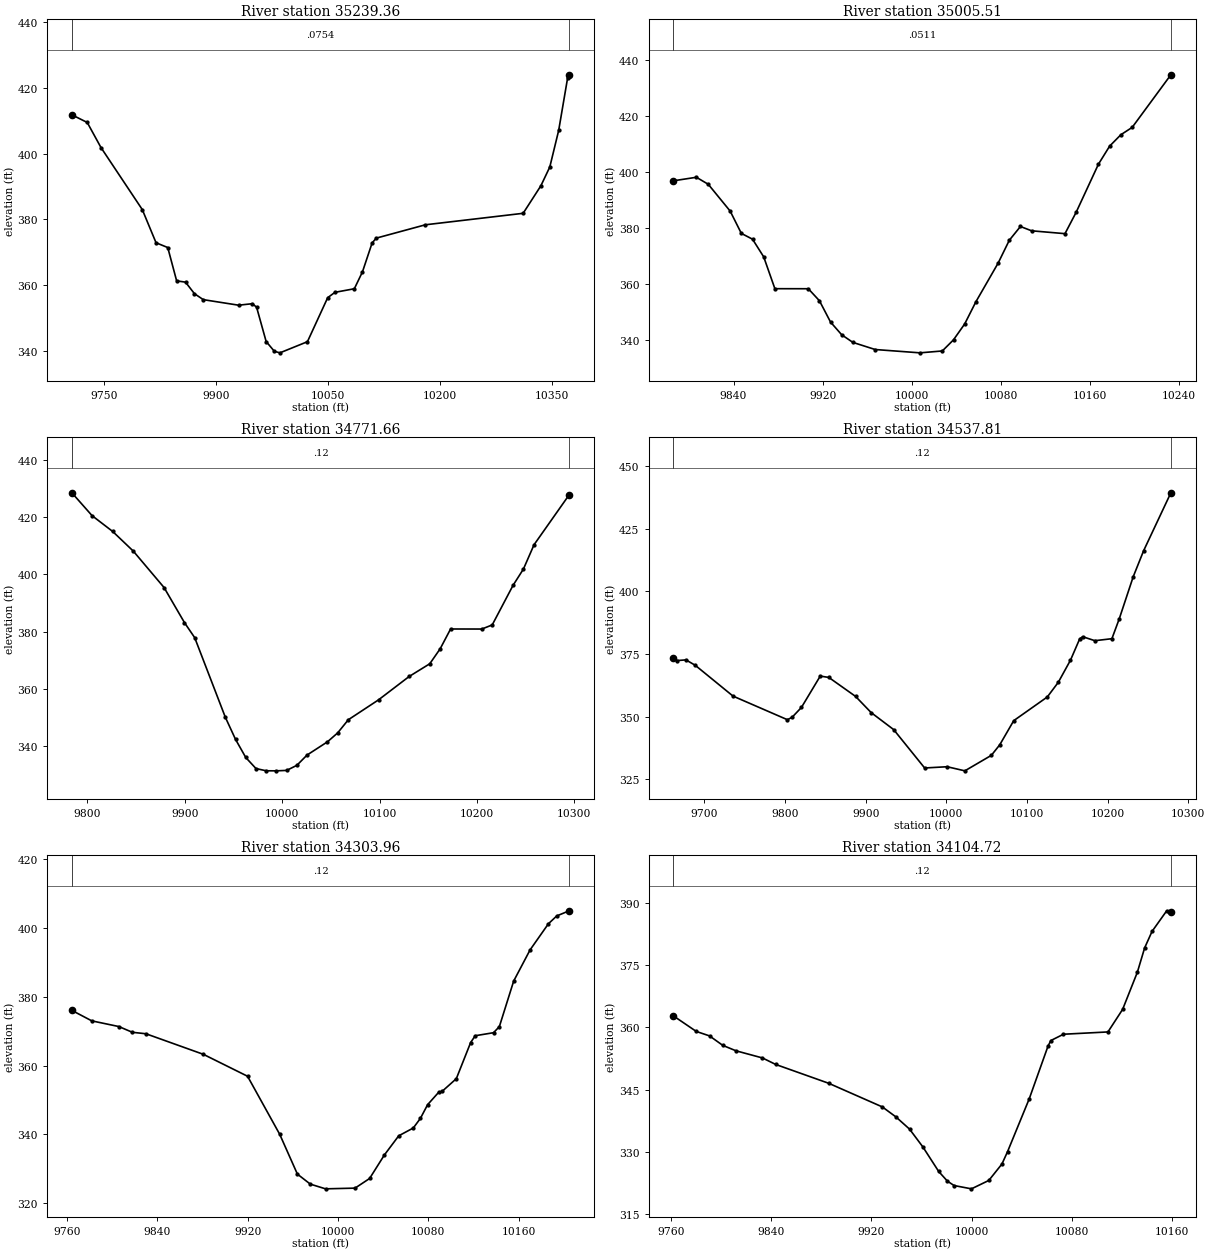
Type RM Length L Ch R = 1 ,35239.36,233.850300,233.850300,233.850300
XS GIS Cut Line= 2
823926.180246631728482.953772997 823564.76341416727923.111227752
#Sta/Elev= 30
9706.362411.85049726.976409.51219745.413401.86479800.726382.96739819.164372.8596
9834.857371.3998 9846.76361.24359858.662360.85739870.565357.34689882.468355.5221
 9929.79353.83139948.228354.28889953.885353.21119966.665342.7625 9977.69339.7777
9985.103339.314210021.98342.707910049.11356.120810058.85357.754710084.82358.8448
10095.73364.009910108.62372.791710114.17374.268710180.04378.335810310.97381.8334
10334.77390.236310346.68395.946810358.58407.093410370.48422.997910372.73424.0467
#Mann= 3 , 0 , 0
9706.362  0.0754       09706.362  0.0754       010372.73  0.0754       0
#XS Ineff= 2 , 0
       09946.961        10041.71       0
Bank Sta=9706.362,10372.73
Exp/Cntr=0.3,0.1

Type RM Length L Ch R = 1 ,35005.51,233.850200,233.850200,233.850200
XS GIS Cut Line= 6
824000.753566356728425.176455903823987.777060937728328.767713239
823987.531708334728284.948277376824001.536006449728096.171085976
823996.402941571728025.805762434823988.215544675727980.787759751
#Sta/Elev= 30
9786.014396.8231 9806.58398.07759817.268395.57459836.947385.99769846.993 378.027
9857.039 375.9599867.084369.6433 9877.13358.27189907.159358.25789917.159353.9662
9927.159346.3451 9937.18341.80449947.202339.08859967.251336.540310007.48335.3557
10027.58 336.02510037.63340.002810047.69345.686310057.74353.592610077.76367.4372
10087.76375.573910097.77380.494210107.77 378.958 10137.8377.933210147.81385.5542
10167.89402.779310177.94409.213710188.01413.275110198.17415.901510232.94434.6956
#Mann= 3 , 0 , 0
9786.014  0.0511       09786.014  0.0511       010232.94  0.0511       0
#XS Ineff= 2 , 0
       0                               0
Bank Sta=9786.014,10232.94
Exp/Cntr=0.3,0.1

Type RM Length L Ch R = 1 ,34771.66,233.850300,233.850300,233.850300
XS GIS Cut Line= 6
824292.408115469728414.622077438824268.755287009728346.578018374
824225.082646366 728208.45097553824183.116296819728074.991254903
824145.104188134727973.981445118824126.556959868727931.945540509
#Sta/Elev= 30
9784.095 428.4619804.869420.47629826.043414.95259847.217408.09099878.762395.3971
9899.736383.14499910.224377.90369941.685350.12049952.172342.39449962.659336.0839
9973.146332.22319983.634331.44649994.121331.426910004.62331.5761 10015.1333.3466
10025.58336.938410046.55341.555810057.03344.672810067.95349.256410098.96356.1956
10130.41364.352410151.58368.795410162.26374.025310172.95380.9289   10205380.9103
10215.69382.346210237.05396.143810247.74401.850810258.64410.332910294.77427.7818
#Mann= 3 , 0 , 0
9784.095    0.12       09784.095    0.12       010294.77    0.12       0
#XS Ineff= 2 , 0
       0                               0
Bank Sta=9784.095,10294.77
Exp/Cntr=0.3,0.1

Type RM Length L Ch R = 1 ,34537.81,233.850300,233.850300,233.850300
XS GIS Cut Line= 6
824618.959649228728358.453975066824541.857398669728233.275431944
824501.576067433728177.968677261824461.479614389728129.159997311
824332.093042599727992.861305542824234.294863211727878.757229444
#Sta/Elev= 30
9661.596373.38639665.565372.35859677.055 372.6339688.545370.49199735.457358.1628
9802.811348.74299808.657349.67879820.305 353.6449843.637366.16469854.276365.6237
9887.437 358.0479906.803351.56829934.698344.78099973.108329.4441   10001329.9434
10022.99328.303510055.86334.496810066.27338.7042 10083.6348.352310125.22357.8123
 10138.9  363.6910154.01372.535310165.35380.986910169.12381.899410184.23380.3062
10205.37381.104610214.45 389.01710231.85 405.90410244.72416.2679 10278.5439.4084
#Mann= 3 , 0 , 0
9661.596    0.12       09661.596    0.12       0 10278.5    0.12       0
#XS Ineff= 2 , 0
       09929.337                       0
Bank Sta=9661.596,10278.5
Exp/Cntr=0.3,0.1

Type RM Length L Ch R = 1 ,34303.96,199.241600,199.241600,199.241600
XS GIS Cut Line= 6
824728.772460098728089.711502876824691.284866931728033.057451057
824666.695101745728001.389223673824613.925963096  727944.4932915
824525.375220434727869.159278986824416.284872805727783.605868264
#Sta/Elev= 30
9764.306376.07929781.947373.03259805.929 371.377 9817.92369.70399829.911369.2805
9880.824363.29349919.948356.91719948.438340.02699964.102328.44949975.515325.5416
9989.013324.166110015.16324.373210028.06327.177910041.18334.032710053.85339.5901
10066.74341.863110073.01344.635810079.45348.651110089.21352.242710092.16352.4837
10104.87356.206110117.58366.735210121.62368.704410137.82 369.58510142.99371.3509
 10155.7384.623910170.23393.685310186.44401.271110193.83403.5558 10204.9405.0532
#Mann= 3 , 0 , 0
9764.306    0.12       09764.306    0.12       0 10204.9    0.12       0
#XS Ineff= 2 , 0
       0                               0
Bank Sta=9764.306,10204.9
Exp/Cntr=0.3,0.1

Type RM Length L Ch R = 1 ,34104.72,512.238800,512.238800,512.238800
XS GIS Cut Line= 6
824804.255163364727982.071761594824760.264249498727853.875780774
824741.423920982727806.654950461824724.324456219727777.866606075
 824695.91636127727748.246265891824582.166390376 727674.08227424
#Sta/Elev= 30
9762.197362.78339780.382 359.0459790.955357.96949801.515355.68559812.074354.3748
9833.193  352.659843.752351.0836 9885.99346.54749928.826340.84229939.592338.4452
9950.502335.49599961.156331.18969973.764325.27889980.738322.94219986.032321.8879
9999.888321.091910013.74323.115710024.23327.086410028.71330.070510045.98342.7951
10061.02355.547410063.25356.852110073.29358.369910108.78358.923710120.49364.3642
10132.21 373.29710138.03379.177610143.93383.153910155.65388.137510158.97387.9428
#Mann= 3 , 0 , 0
9762.197    0.12       09762.197    0.12       010158.97    0.12       0
#XS Ineff= 2 , 0
       0                               0
Bank Sta=9762.197,10158.97
Exp/Cntr=0.3,0.1

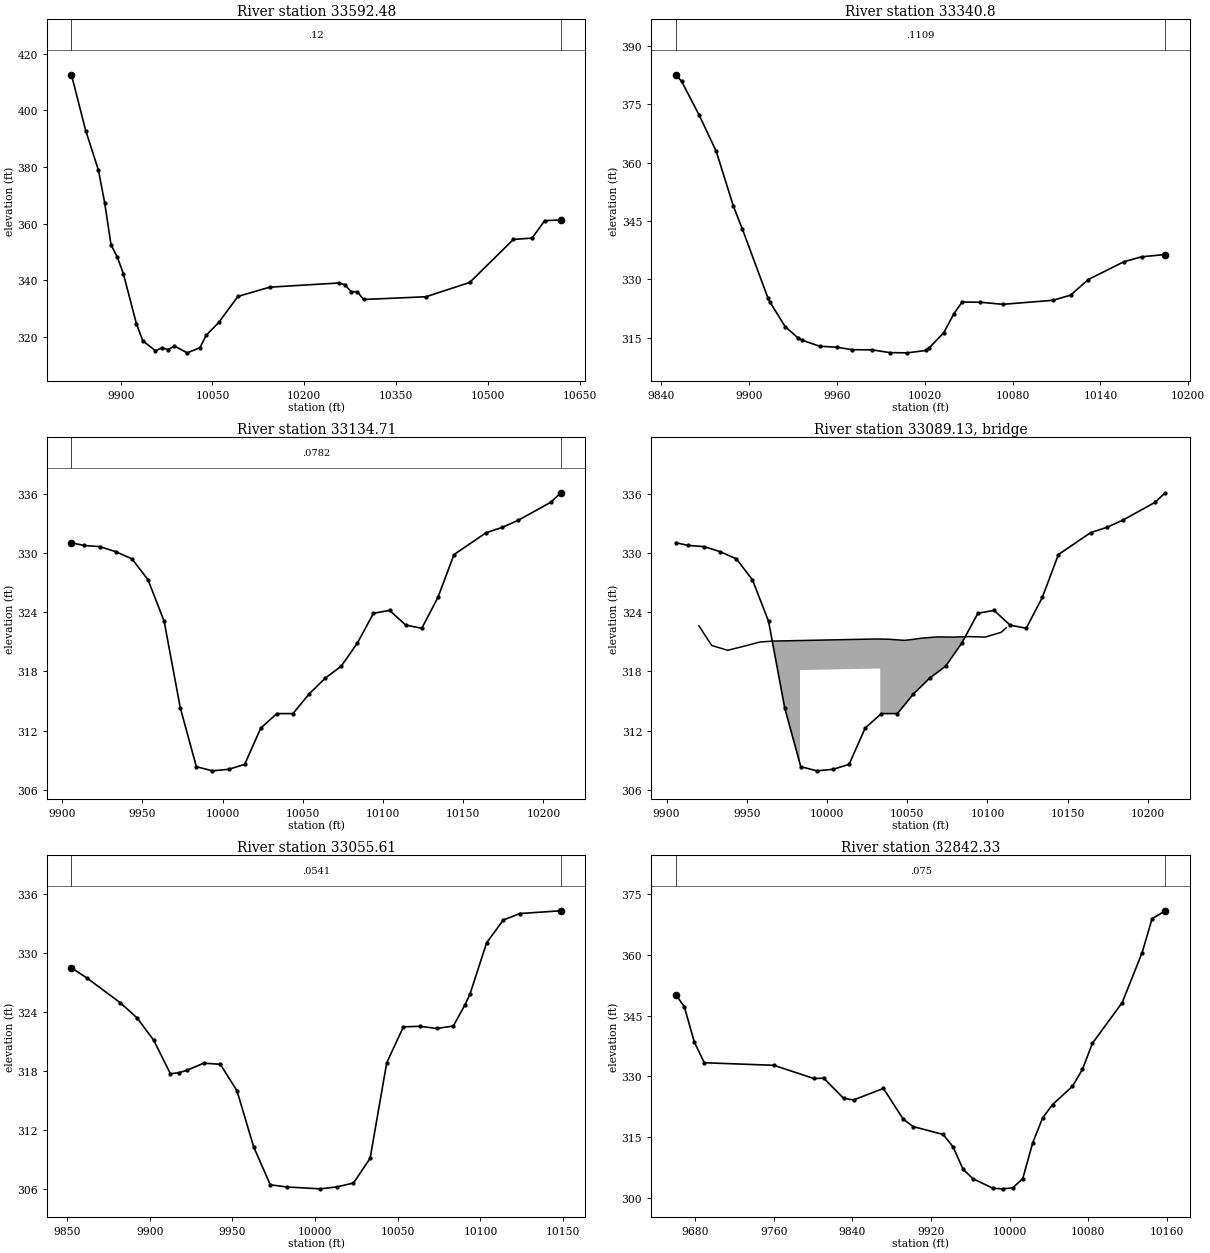
Type RM Length L Ch R = 1 ,33592.48,251.683400,251.683400,251.683400
XS GIS Cut Line= 3
825367.411695526727757.332940321825020.869380132727662.852680046
 824588.84384792727576.765137719
#Sta/Elev= 30
9819.629412.53559842.859392.86539863.589378.98819873.954367.34929884.319352.4896
9894.684348.18719904.533342.27239925.779324.68599936.144318.70049956.874315.1758
9967.239316.20969977.604315.56669987.969316.8569 10008.7314.438610029.43316.2122
10039.79320.617110060.52325.217510091.62334.346510143.44337.603810256.18339.0772
10266.38338.484710276.57336.019410286.77335.947310296.97333.256610398.93334.2271
10470.31339.272110541.69354.447410572.28 354.92910592.67361.049410619.34361.3339
#Mann= 3 , 0 , 0
9819.629    0.12       09819.629    0.12       010619.34    0.12       0
#XS Ineff= 2 , 0
       0                               0
Bank Sta=9819.629,10619.34
Exp/Cntr=0.3,0.1

Type RM Length L Ch R = 1 , 33340.8,206.087500,206.087500,206.087500
XS GIS Cut Line= 6
825248.341985805 727410.92765189825152.885997409727470.501139959
825119.808553509727492.768000073825109.454392378727500.073058824
825048.406265716727545.669132273824971.646709217727598.543445101
#Sta/Elev= 30
 9849.85382.6116 9853.79380.90759865.577372.37649877.365362.98699889.153348.8127
9895.317342.89539912.728325.22749914.205 324.0819924.516 317.8369933.093314.9871
9936.303 314.3129948.091312.77099959.879312.51939970.427311.87669983.932 311.848
9995.986311.127710008.12311.072510020.48311.675410023.15312.417310032.96316.2698
10039.86321.146910045.44324.136210057.92324.089410073.28323.555310107.56324.5933
10119.53325.917410131.68329.932410155.96334.506910168.11335.780210184.32336.3727
#Mann= 3 , 0 , 0
 9849.85  0.1109       0 9849.85  0.1109       010184.32  0.1109       0
#XS Ineff= 2 , 0
       0                10086.63       0
Bank Sta=9849.85,10184.32
Exp/Cntr=0.3,0.1

Type RM Length L Ch R = 1 ,33134.71,79.100100,79.100100,79.100100
XS GIS Cut Line= 2
824971.742906498727287.422933583824946.165231369727591.424664706
#Sta/Elev= 30
9905.798331.05239913.402 330.7769923.437330.65559933.472330.13949943.508329.4146
9953.543327.28749963.578323.08259973.614314.31329983.649308.33669993.684307.9138
10003.72308.068210013.75 308.56910023.79312.249410033.83313.720510043.86313.7172
 10053.9 315.71110063.93317.308610073.97318.5346   10084320.872910094.04323.8942
10104.07324.189310114.11322.696210124.14322.373410134.18 325.49610144.21329.8492
10164.28332.068310174.32 332.60710184.36 333.33510204.43335.147410210.87336.1167
#Mann= 3 , 0 , 0
9905.798  0.0782       09905.798  0.0782       010210.87  0.0782       0
#XS Ineff= 2 , 0
       09975.055        10040.39       0
Bank Sta=9905.798,10210.87
Exp/Cntr=0.3,0.1

Type RM Length L Ch R = 3 ,33089.13,,,
BEGIN DESCRIPTION:
END DESCRIPTION:
Bridge Culvert--1,0,-1,-1, 0
Deck Dist Width WeirC Skew NumUp NumDn MinLoCord MaxHiCord MaxSubmerge Is_Ogee
21.550050,36.000000,2.6,0, 21, 21, , , 0.95, 0, 0,0,,
 9920.19 9928.11 9938.13 9948.16 9958.18 9966.97 9983.17 9983.1710031.1510033.17
10033.1710038.3610048.3910053.2510058.4110068.4310078.4510088.4810098.5010108.52
10111.65
  322.62  320.63  320.14  320.55  320.98  321.08  321.13  321.13  321.29  321.28
  321.28  321.26  321.15  321.24  321.36  321.50  321.48  321.53  321.48  321.96
  322.42
 -677.38 -679.37 -679.86 -679.45 -679.02 -678.92 -678.87  318.13  318.29  318.28
 -678.72 -678.74 -678.85 -678.76 -678.64 -678.50 -678.52 -678.47 -678.52 -678.04
 -677.58
 9920.19 9928.11 9938.13 9948.16 9958.18 9966.97 9976.10 9976.1010026.1010026.10
10031.1510038.3610048.3910053.2510058.4110068.4310078.4510088.4810098.5010108.52
10111.65
  322.62  320.63  320.14  320.55  320.98  321.08  321.11  321.11  321.27  321.27
  321.29  321.26  321.15  321.24  321.36  321.50  321.48  321.53  321.48  321.96
  322.42
 -677.38 -679.37 -679.86 -679.45 -679.02 -678.92 -678.89  318.11  318.27 -678.73
 -678.71 -678.74 -678.85 -678.76 -678.64 -678.50 -678.52 -678.47 -678.52 -678.04
 -677.58
BR Coef=-1 , 0 , 0 ,, 0 ,,,0.8,0,1,0,
WSPro=,,,, 1 ,,,, 0 ,,,, 0 ,,,,-1 ,-1 ,-1 , 0 , 0 , 0 , 0 , 0
BC Design=,, 0 ,, 0 ,,,,,,

Type RM Length L Ch R = 1 ,33055.61,213.280300,213.280300,213.280300
XS GIS Cut Line= 2
824902.521405831727235.535005657824868.300362339727529.665692571
#Sta/Elev= 29
9852.589328.48319862.118327.41869882.253324.9095 9892.32323.37759902.388 321.104
9912.455317.69889917.672 317.8139922.523318.0575 9932.59318.78029942.658318.6609
9952.725315.97219962.793310.2823 9972.86306.40749982.927306.185810003.06305.9952
10013.13306.1921 10023.2306.584110033.26309.100110043.33318.8322 10053.4 322.473
10063.47322.530610073.53 322.306 10083.6322.559110090.73324.739210093.67325.8022
10103.74331.0188 10113.8333.340810123.87334.0003 10148.7334.2806
#Mann= 3 , 0 , 0
9852.589  0.0541       09852.589  0.0541       0 10148.7  0.0541       0
#XS Ineff= 2 , 0
       09968.566        10032.27       0
Bank Sta=9852.589,10148.7
Exp/Cntr=0.3,0.1

Type RM Length L Ch R = 1 ,32842.33,280.641800,280.641800,280.641800
XS GIS Cut Line= 2
825113.585985498727162.717437205824621.669899197727241.431542676
#Sta/Elev= 30
9660.226350.25199668.922347.15089679.049338.47379689.176333.39739760.067332.7621
9800.575329.50699810.703329.57229830.957324.60849841.084324.19859871.466327.0534
 9891.72319.43599901.848317.61789932.229315.67669942.356  312.629952.484307.0887
9962.611304.74469982.865302.37639992.993302.240910003.12302.486610013.25304.7575
10023.37313.5757 10033.5319.774210043.63323.074610063.88327.565510074.01331.7576
10084.14338.177710114.52348.276310134.77360.6012 10144.9368.9778 10158.4370.9428
#Mann= 3 , 0 , 0
9660.226   0.075       09660.226   0.075       0 10158.4   0.075       0
#XS Ineff= 2 , 0
       09906.742                       0
Bank Sta=9660.226,10158.4
Exp/Cntr=0.3,0.1

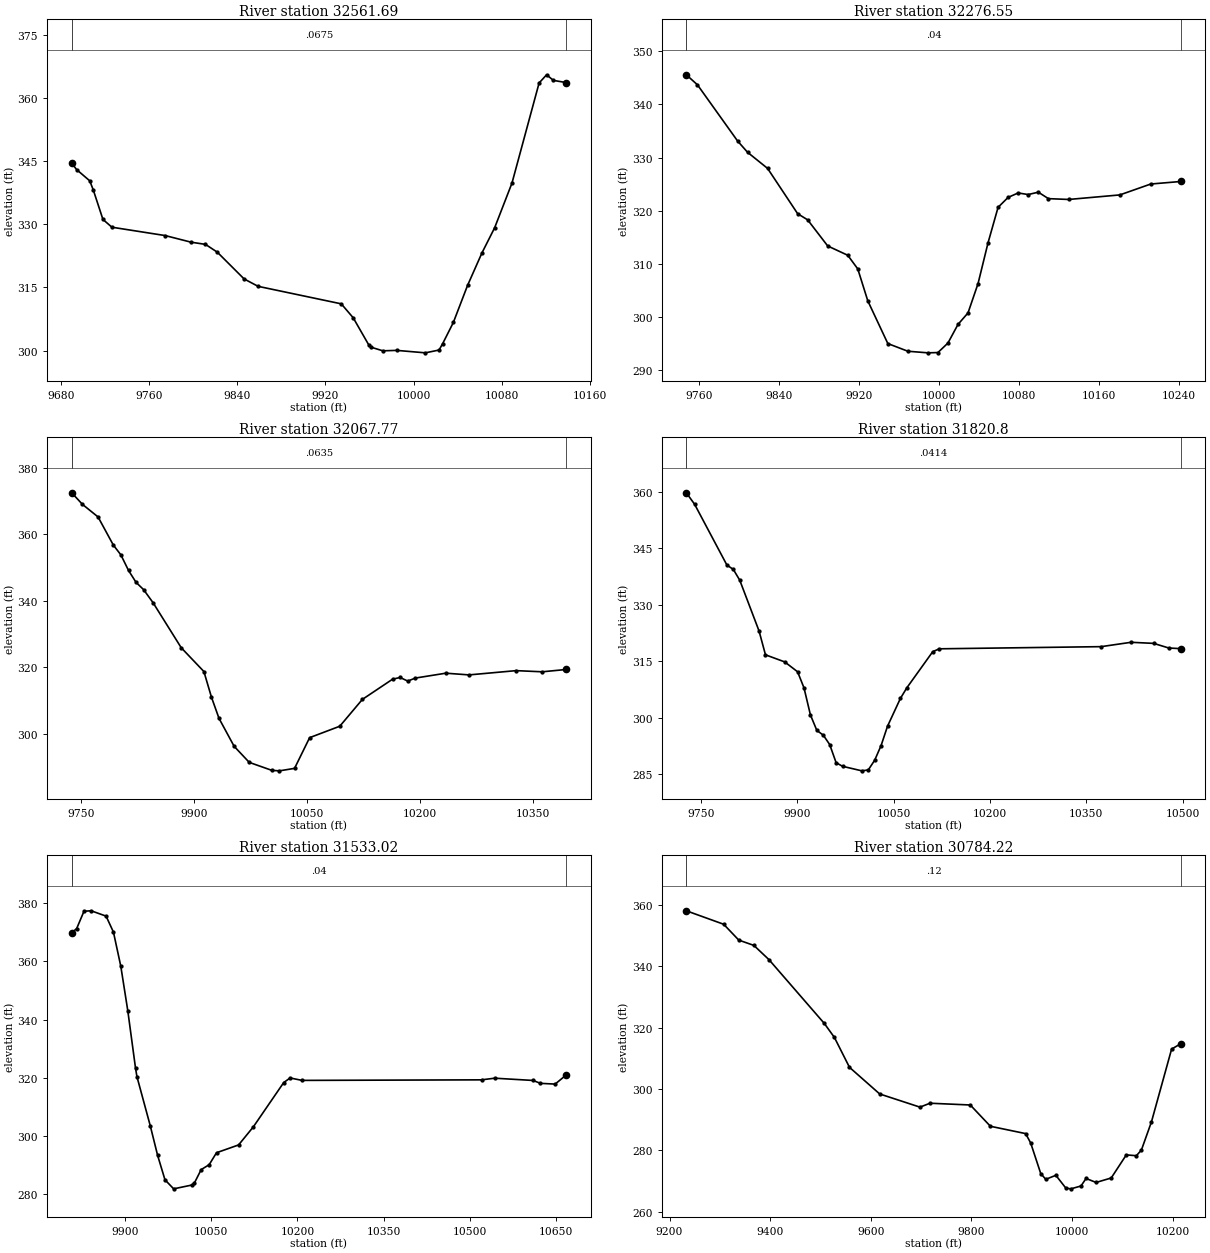
Type RM Length L Ch R = 1 ,32561.69,285.134200,285.134200,285.134200
XS GIS Cut Line= 6
825108.729864797727125.772840988825078.185628099727105.846862304
825035.861124619727084.721627267824976.073412828727045.713927377
824851.881427698726951.053041826824746.220420507726863.625260136
#Sta/Elev= 30
9689.915 344.5079694.369342.97719706.308340.30479709.632338.03519718.248331.1508
9726.384329.3034  9774.7327.32219798.192325.75169811.281325.23169822.024323.3741
9846.282317.03689859.026315.27329934.456311.12119945.285307.8104  9959.6301.2818
9961.786300.80889972.172 299.9759984.743300.078110010.77299.495710023.15300.1631
10026.48301.694310036.12306.701310049.08315.533510062.05 323.189 10073.6329.1793
10089.31339.771310113.92363.528810120.73365.470810126.88364.1397 10138.4363.6265
#Mann= 3 , 0 , 0
9689.915  0.0675       09689.915  0.0675       0 10138.4  0.0675       0
#XS Ineff= 2 , 0
       0                               0
Bank Sta=9689.915,10138.4
Exp/Cntr=0.3,0.1

Type RM Length L Ch R = 1 ,32276.55,208.788000,208.788000,208.788000
XS GIS Cut Line= 6
825120.754829747 727106.10786123 825106.02591322726835.373850703
825101.860771399726768.192420739825091.820267193726703.628276458
825075.664731489726638.230109376825068.391122913726616.471050573
#Sta/Elev= 30
9747.488345.58519758.613343.69769798.672333.12939808.687330.98739828.717  327.95
9858.761 319.4189868.776318.25589888.806313.33859908.835311.5877 9918.85309.0169
9928.865303.00229948.895294.95359968.924 293.5099988.954293.20719998.969 293.262
10008.98295.0534   10019298.556310029.02300.728610039.04 306.24410049.06313.9488
10059.07320.616710069.09322.484710079.11323.322210089.16323.025610099.28 323.469
 10109.4322.253910129.64322.098810180.76322.954410211.66325.007310241.58325.4828
#Mann= 3 , 0 , 0
9747.488    0.04       09747.488    0.04       010241.58    0.04       0
#XS Ineff= 2 , 0
       0                               0
Bank Sta=9747.488,10241.58
Exp/Cntr=0.3,0.1

Type RM Length L Ch R = 1 ,32067.77,246.961100,246.961100,246.961100
XS GIS Cut Line= 6
 825320.98414733727138.320983426825303.138963673727032.433222623
825319.178447929726791.285640779825316.089313823726716.773599031
825293.008311833 726592.47402475825258.197091574726492.639492156
#Sta/Elev= 30
9737.065372.44829751.365368.96699772.069365.18879792.314356.76219802.417353.7849
 9812.52349.12759822.531345.54299832.539343.36219845.116339.43569882.562325.9009
9912.675 318.7519922.713311.05489932.752304.67839952.829296.29189972.906291.4634
10003.02289.058510013.05288.9218 10033.1289.666510053.12298.891410093.16302.3177
10123.19 310.38310163.24 316.44210173.34 316.97210183.44315.882310193.54316.7893
10234.06318.254210264.86317.740610327.38319.022810362.07318.672410393.79319.3642
#Mann= 3 , 0 , 0
9737.065  0.0635       09737.065  0.0635       010393.79  0.0635       0
#XS Ineff= 2 , 0
       0                               0
Bank Sta=9737.065,10393.79
Exp/Cntr=0.3,0.1

Type RM Length L Ch R = 1 , 31820.8,287.784200,287.784200,287.784200
XS GIS Cut Line= 6
825568.560887815 727147.78475059825558.915498295727029.945935513
825560.518450455726846.868078394825544.005861979726722.028944375
825491.635442348726594.955271329825387.194958764726419.162965753
#Sta/Elev= 30
9727.252359.72589740.149356.68789790.465340.55229800.477339.39139810.489 336.529
9840.524323.0596 9850.53316.73759880.533314.85519900.535312.23689910.536 307.954
9920.537300.78639930.538296.67479940.538295.42579950.539292.9293 9960.54288.1119
9970.541287.159710000.54285.956210010.54286.188510020.55288.759110030.55292.6619
10040.57297.7919 10060.6305.159510070.62307.977410110.94317.5611 10121.1318.3303
10373.22318.903110419.77 320.059   10455319.771310478.48318.546610497.08318.3723
#Mann= 3 , 0 , 0
9727.252  0.0414       09727.252  0.0414       010497.08  0.0414       0
#XS Ineff= 2 , 0
       0                               0
Bank Sta=9727.252,10497.08
Exp/Cntr=0.3,0.1

Type RM Length L Ch R = 1 ,31533.02,748.796400,748.796400,748.796400
XS GIS Cut Line= 2
825966.167056712727031.704885155825427.115520758726360.158497455
#Sta/Elev= 30
9806.775369.90199815.373 371.2829828.196377.2735 9840.59377.42589866.666 375.591
9879.489370.09569892.312358.3521 9904.49343.05399917.958323.30379920.465320.3684
9943.605303.53349956.428 293.3449969.251284.94789984.365281.846110016.31283.1633
10020.54283.871310032.29288.454510046.19290.138110059.01294.254710097.48296.9384
10123.13303.145310176.06 318.38110187.24319.956210208.01319.123910520.65 319.312
10543.49319.878110610.41319.103910623.23318.106910648.88317.852610667.91320.9626
#Mann= 3 , 0 , 0
9806.775    0.04       09806.775    0.04       010667.91    0.04       0
#XS Ineff= 2 , 0
       0                               0
Bank Sta=9806.775,10667.91
Exp/Cntr=0.3,0.1

Type RM Length L Ch R = 1 ,30784.22,509.809200,509.809200,509.809200
XS GIS Cut Line= 2
826005.803428902726979.251295444826035.881188866 725996.93830378
#Sta/Elev= 30
9233.284358.0833 9307.57353.69089337.584348.53089367.598346.80079397.612342.1608
9507.664321.36729527.673316.81749557.687307.07189617.715298.39719697.753294.1058
9717.762295.37919797.799294.80369837.818287.86689907.851285.48239917.856282.4224
9937.865272.4607 9947.87270.58469967.879271.89419987.888267.69699997.893267.4838
 10017.9268.418710027.91270.864610047.92269.565810077.93271.021710107.94278.5452
10127.95278.276110137.96280.121510157.97289.324110197.99313.020410216.06314.7506
#Mann= 3 , 0 , 0
9233.284    0.12       09233.284    0.12       010216.06    0.12       0
#XS Ineff= 2 , 0
       0                 10087.5       0
Bank Sta=9233.284,10216.06
Exp/Cntr=0.3,0.1

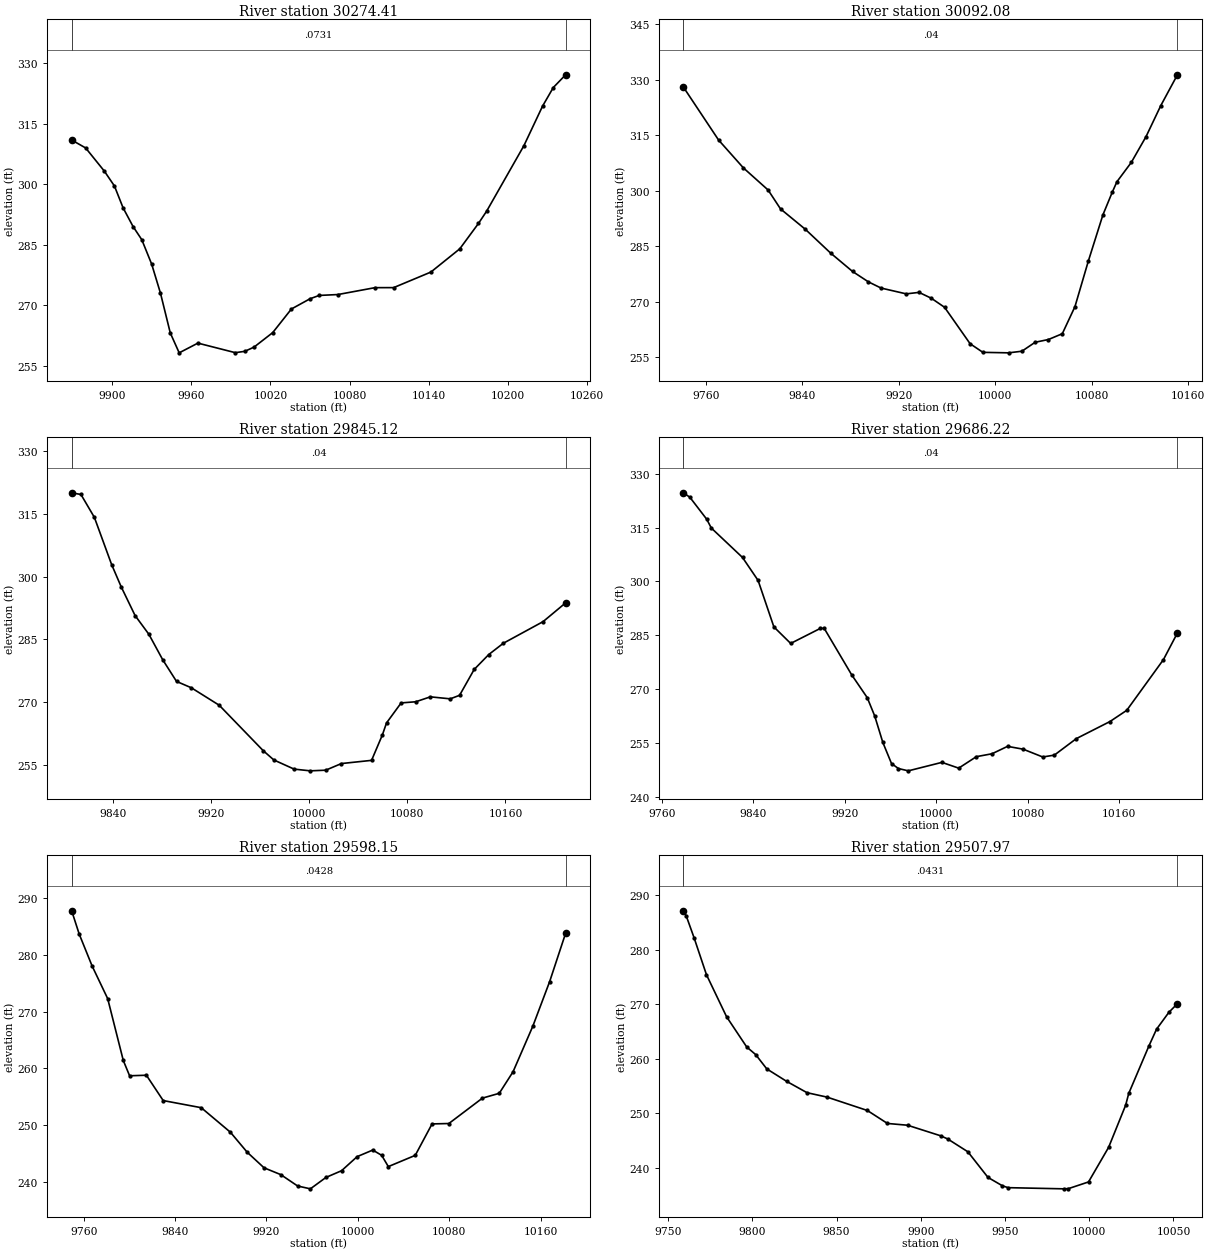
Type RM Length L Ch R = 1 ,30274.41,182.337700,182.337700,182.337700
XS GIS Cut Line= 3
826067.523492873726747.976424715826327.293465564726486.921682585
826332.112160812726483.168347624
#Sta/Elev= 30
9869.323310.93229879.923308.9632  9894.1303.21779901.737299.54289908.277294.1408
9915.845289.50579922.454286.25249929.952 280.1979936.632272.99339944.059 263.148
9950.809 258.2259964.986260.6311 9993.34258.266610000.49258.595610007.52259.6384
10021.69263.231510035.87269.083910050.05271.627910056.92272.441810071.03 272.659
10099.24274.368110113.35274.375610141.56278.225710163.47283.980810177.64290.2695
10183.88293.3353 10212.1309.542610226.21319.318210234.35323.926310243.71327.0878
#Mann= 3 , 0 , 0
9869.323  0.0731       09869.323  0.0731       010243.71  0.0731       0
#XS Ineff= 2 , 0
       0                               0
Bank Sta=9869.323,10243.71
Exp/Cntr=0.3,0.1

Type RM Length L Ch R = 1 ,30092.08,246.961000,246.961000,246.961000
XS GIS Cut Line= 6
 826252.47999228726983.735311099826274.227743816726882.407018377
826322.079763009726736.306699597826349.415290851726674.896217747
826369.581064331 726640.57716644826395.435874039726603.695708597
#Sta/Elev= 30
9741.545328.0153 9770.67313.72939791.159306.22319811.725300.22139822.007295.1183
9842.573289.61149863.459283.20319881.694278.21729894.862275.39999905.329273.7263
9926.264272.15139936.843272.5543 9947.11270.95639958.023268.52249979.204258.6736
9989.794256.347910011.13256.213810022.13256.650810033.13259.071710044.13259.8121
10055.64261.383710066.12268.693810077.26281.059810089.31293.5041   10097299.5918
10100.91302.450110112.85307.685210125.07314.659210137.28323.025610151.08 331.366
#Mann= 3 , 0 , 0
9741.545    0.04       09741.545    0.04       010151.08    0.04       0
#XS Ineff= 2 , 0
       0                               0
Bank Sta=9741.545,10151.08
Exp/Cntr=0.3,0.1

Type RM Length L Ch R = 1 ,29845.12,158.891100,158.891100,158.891100
XS GIS Cut Line= 6
 826431.87332104727031.923048608826447.558352183 726996.32140851
826469.856605655726953.198843062826493.182412352726913.898634733
826565.311364827726817.374284358826644.439460607726691.421167177
#Sta/Elev= 30
9806.605320.0346 9814.17319.62379825.098314.16429839.163 302.8829846.996297.5452
9858.254290.72169869.512286.2377 9880.77280.16669892.028 274.9869904.132273.4587
9926.847269.28839962.697258.43319971.325256.22729987.837254.0378   10001 253.626
 10013.6253.780510026.38255.365510050.96256.128810059.79  262.2210063.15265.0679
10075.06269.848210086.96270.123810098.86271.299610115.06270.822610122.67271.6634
10134.57 277.84410146.47281.4074 10158.3 284.09110190.71289.261410209.09293.7485
#Mann= 3 , 0 , 0
9806.605    0.04       09806.605    0.04       010209.09    0.04       0
#XS Ineff= 2 , 0
       0                               0
Bank Sta=9806.605,10209.09
Exp/Cntr=0.3,0.1

Type RM Length L Ch R = 1 ,29686.22,88.070000,88.070000,88.070000
XS GIS Cut Line= 2
826521.188222963727092.874550531826815.163934775 726776.04876293
#Sta/Elev= 30
9778.955324.67999784.559323.42969799.262317.33049803.339314.85819830.623306.6625
9844.264 300.262 9858.07287.32339872.772282.71989898.831286.92759902.176286.8834
9926.115273.99099939.756267.61869946.282262.52969953.398255.15369960.984249.2754
 9967.04247.87769975.686247.237910005.09 249.59510019.79247.989510035.25251.1888
10048.89251.986710062.53254.055110076.17253.2686 10093.3251.098510103.46251.6141
10122.71256.212410152.11260.964210166.81264.088310198.95278.228310211.16285.6475
#Mann= 3 , 0 , 0
9778.955    0.04       09778.955    0.04       010211.16    0.04       0
#XS Ineff= 2 , 0
       0                               0
Bank Sta=9778.955,10211.16
Exp/Cntr=0.3,0.1

Type RM Length L Ch R = 1 ,29598.15,90.181200,90.181200,90.181200
XS GIS Cut Line= 2
826570.529110978 727168.10117953826864.504722527726851.275990333
#Sta/Elev= 30
 9749.54287.80499756.113283.70199767.412278.06949781.054272.30729794.696261.4066
9800.219258.70819814.921258.80219829.623254.33589862.904253.07749888.431248.7501
9903.133245.22149917.835242.47959932.537241.27039947.239239.26999958.396238.7683
9972.038240.78229985.679241.96439999.321244.448810012.96245.605810020.75244.6822
 10026.6242.689310050.15244.672710064.86250.216810079.56250.287710108.96254.7683
10123.66255.615210135.74259.418310153.07267.469910167.77275.325610181.74283.8545
#Mann= 3 , 0 , 0
 9749.54  0.0428       0 9749.54  0.0428       010181.74  0.0428       0
#XS Ineff= 2 , 0
       0                               0
Bank Sta=9749.54,10181.74
Exp/Cntr=0.3,0.1

Type RM Length L Ch R = 1 ,29507.97,158.914900,158.914900,158.914900
XS GIS Cut Line= 2
826573.551171163727198.420610608826819.215361044727038.220988398
#Sta/Elev= 30
9759.088  287.129760.818286.1085 9765.35282.20329772.756275.37649784.694 267.668
9796.633262.12739801.965260.72549808.571258.09739820.272255.82749832.448253.7323
9844.386252.91829868.263 250.4679880.201248.0863 9892.14247.76019911.809245.8202
9916.016245.23479927.955242.88489939.893238.18179948.424236.65149951.831236.3014
9985.038 236.0869987.647236.12449999.585237.351710011.52 243.70410021.65251.4519
10023.46 253.592 10035.4 262.27810039.96265.379510047.34268.499310052.37270.0645
#Mann= 3 , 0 , 0
9759.088  0.0431       09759.088  0.0431       010052.37  0.0431       0
#XS Ineff= 2 , 0
       0                               0
Bank Sta=9759.088,10052.37
Exp/Cntr=0.3,0.1

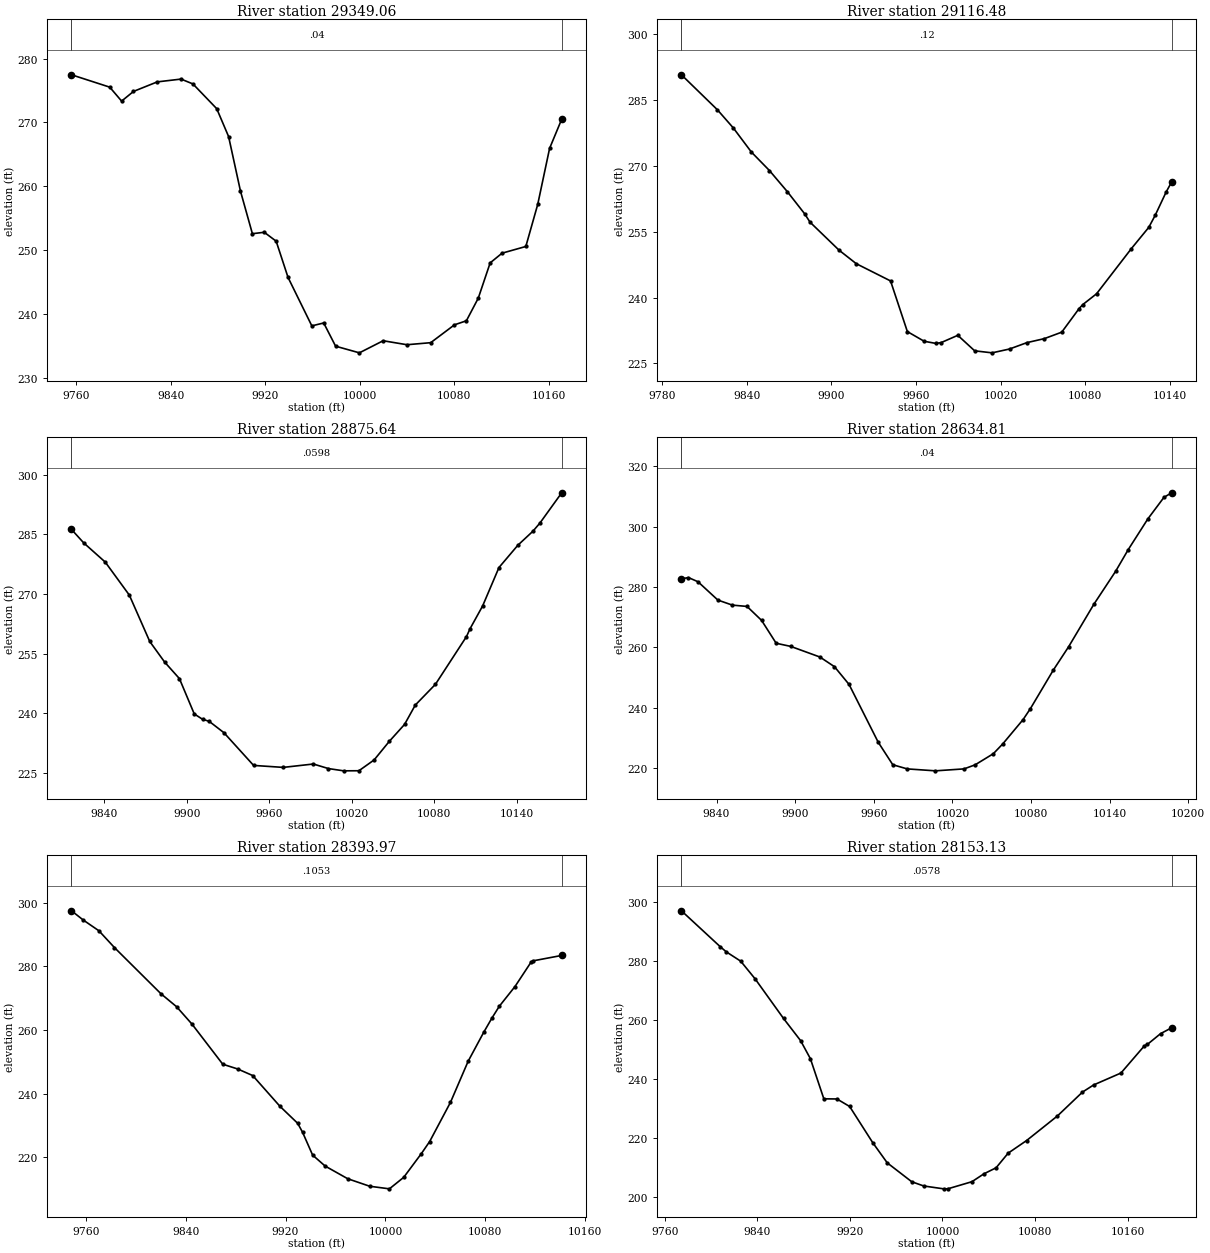
Type RM Length L Ch R = 1 ,29349.06,232.577600,232.577600,232.577600
XS GIS Cut Line= 2
826817.653403434 727437.15824478826864.665270895727024.801277526
#Sta/Elev= 30
9756.087277.45729788.454  275.529798.519273.33489808.583274.85189828.713276.3452
9848.843 276.7839858.907276.02219879.037272.14949889.102267.77919899.166259.2278
9909.231252.57249919.296 252.7949929.361251.39989939.426245.71979959.555238.1397
 9969.62238.59239979.685234.95719999.814233.915710019.94235.809210040.07235.1871
 10060.2235.506110080.33238.3046 10090.4238.935110100.46242.475810110.53248.0025
10120.59249.520910140.72250.571510150.79257.152310160.85 265.93710171.12270.5115
#Mann= 3 , 0 , 0
9756.087    0.04       09756.087    0.04       010171.12    0.04       0
#XS Ineff= 2 , 0
       0                               0
Bank Sta=9756.087,10171.12
Exp/Cntr=0.3,0.1

Type RM Length L Ch R = 1 ,29116.48,240.836800,240.836800,240.836800
XS GIS Cut Line= 6
827193.853229553727180.835947835827136.405555405727135.228585728
827080.456209825727095.921685432827027.146700035  727061.3970023
827025.495861096727060.267962457 826911.85581546726978.147656152
#Sta/Elev= 30
 9793.76290.76519819.229282.80519830.601278.63039843.369273.15489856.137268.9556
9868.828264.1426 9881.05259.12099884.904257.19649905.492250.80869917.713247.7277
9941.988243.80359953.902232.26539965.816230.05899973.976229.5793 9977.73229.7405
9989.644231.411510001.61227.881110013.95227.423710026.29228.294710038.63229.7492
10050.96230.6586 10063.3 232.13110075.64237.516810078.29238.432510087.98240.8751
10112.65251.161910124.99256.003910129.51 258.72810137.33264.072410141.21266.3462
#Mann= 3 , 0 , 0
 9793.76    0.12       0 9793.76    0.12       010141.21    0.12       0
#XS Ineff= 2 , 0
       0                               0
Bank Sta=9793.76,10141.21
Exp/Cntr=0.3,0.1

Type RM Length L Ch R = 1 ,28875.64,240.836800,240.836800,240.836800
XS GIS Cut Line= 6
827257.598521359726901.176850261827109.554998614726840.813297985
827027.971956692726802.476716649826992.689314877 726783.97394704
826963.441075685726765.157415949826939.038879283726744.649252566
#Sta/Elev= 30
9816.237286.26639825.066282.89269840.803278.02939858.296269.71699873.165 258.025
9883.952252.8519 9894.74248.66869905.527239.77079911.628238.40689916.314237.9254
9927.101235.04469948.676226.8001 9970.25226.30239992.123227.153710003.13226.0036
 10014.2225.434110025.27 225.45710036.34228.181110047.42232.882310058.49  237.14
10066.27242.005710080.92247.2333 10103.5259.261610106.11261.248710115.25266.9807
10127.14 276.66810140.89282.285910151.81285.808510156.88 287.84910172.78295.4986
#Mann= 3 , 0 , 0
9816.237  0.0598       09816.237  0.0598       010172.78  0.0598       0
#XS Ineff= 2 , 0
       0                               0
Bank Sta=9816.237,10172.78
Exp/Cntr=0.3,0.1

Type RM Length L Ch R = 1 ,28634.81,240.836800,240.836800,240.836800
XS GIS Cut Line= 6
827349.773835897726690.839708653827198.398726296726616.518921228
827146.857634925726594.823942313827102.870741742726571.122715876
827068.431780279726550.258419683827020.242522798 726515.66543294
#Sta/Elev= 30
9813.185282.69449818.566283.10849825.836281.72629841.014275.66369852.137273.9863
9863.259273.56329874.382268.94059885.504261.37729896.627260.33679918.872256.8275
9929.995253.62669941.117247.76189963.362228.64669974.485221.19079985.491219.8145
10007.07219.171510028.88219.818110037.32221.156310051.23224.840910058.47228.1055
10073.95236.136610079.55239.773110096.93252.453310108.62260.179510127.99274.3017
10144.52285.158110154.18292.358810169.13302.508810181.43309.641410187.31 311.159
#Mann= 3 , 0 , 0
9813.185    0.04       09813.185    0.04       010187.31    0.04       0
#XS Ineff= 2 , 0
       0                               0
Bank Sta=9813.185,10187.31
Exp/Cntr=0.3,0.1

Type RM Length L Ch R = 1 ,28393.97,240.836900,240.836900,240.836900
XS GIS Cut Line= 6
827492.440697112726542.268390547827401.601626856726474.670194112
827300.233699982726407.484435181 827276.26786421726387.484987319
 827198.32535161726328.970123791 827176.48146297726309.766329002
#Sta/Elev= 30
9748.545297.47629757.954294.56959770.535291.17799782.967285.90079820.261271.3621
9832.692267.31899845.124261.8072  9869.7 249.2329881.697247.72939893.694245.6624
9915.485236.00489929.685 230.6619933.586227.86519941.682220.65369951.687217.2145
9969.788213.22449987.407210.859710003.18210.046910014.64213.664610028.73221.1042
10035.43 224.93110052.09237.247710066.24250.165510078.75259.3006 10085.4263.8226
10091.25267.482910103.76273.658710116.53 281.27310118.11281.724210141.19283.4346
#Mann= 3 , 0 , 0
9748.545  0.1053       09748.545  0.1053       010141.19  0.1053       0
#XS Ineff= 2 , 0
       0                               0
Bank Sta=9748.545,10141.19
Exp/Cntr=0.3,0.1

Type RM Length L Ch R = 1 ,28153.13,240.836800,240.836800,240.836800
XS GIS Cut Line= 6
827586.840788685726464.483759671827534.252413191726397.914601185
 827511.64946528 726359.78189958827486.121849849726296.985354919
827457.454931633726199.672089393827403.589135729  726086.6427798
#Sta/Elev= 30
9774.238296.89189807.788284.73839813.064282.98379825.522279.82999837.933273.8643
9862.525260.44579877.282252.94599885.774246.81419897.399 233.2359908.722233.1865
9919.716230.63919939.675218.39329952.229211.55739973.386205.16869983.787203.7303
   10001202.763410004.59202.770410025.46205.1814 10035.9207.864210046.34209.8902
10056.77214.840410072.77219.126810099.36227.426910121.04235.517610130.71 237.936
10154.32241.969710174.59251.182710177.16251.645510188.59255.306910198.15257.2795
#Mann= 3 , 0 , 0
9774.238  0.0578       09774.238  0.0578       010198.15  0.0578       0
#XS Ineff= 2 , 0
       0                               0
Bank Sta=9774.238,10198.15
Exp/Cntr=0.3,0.1