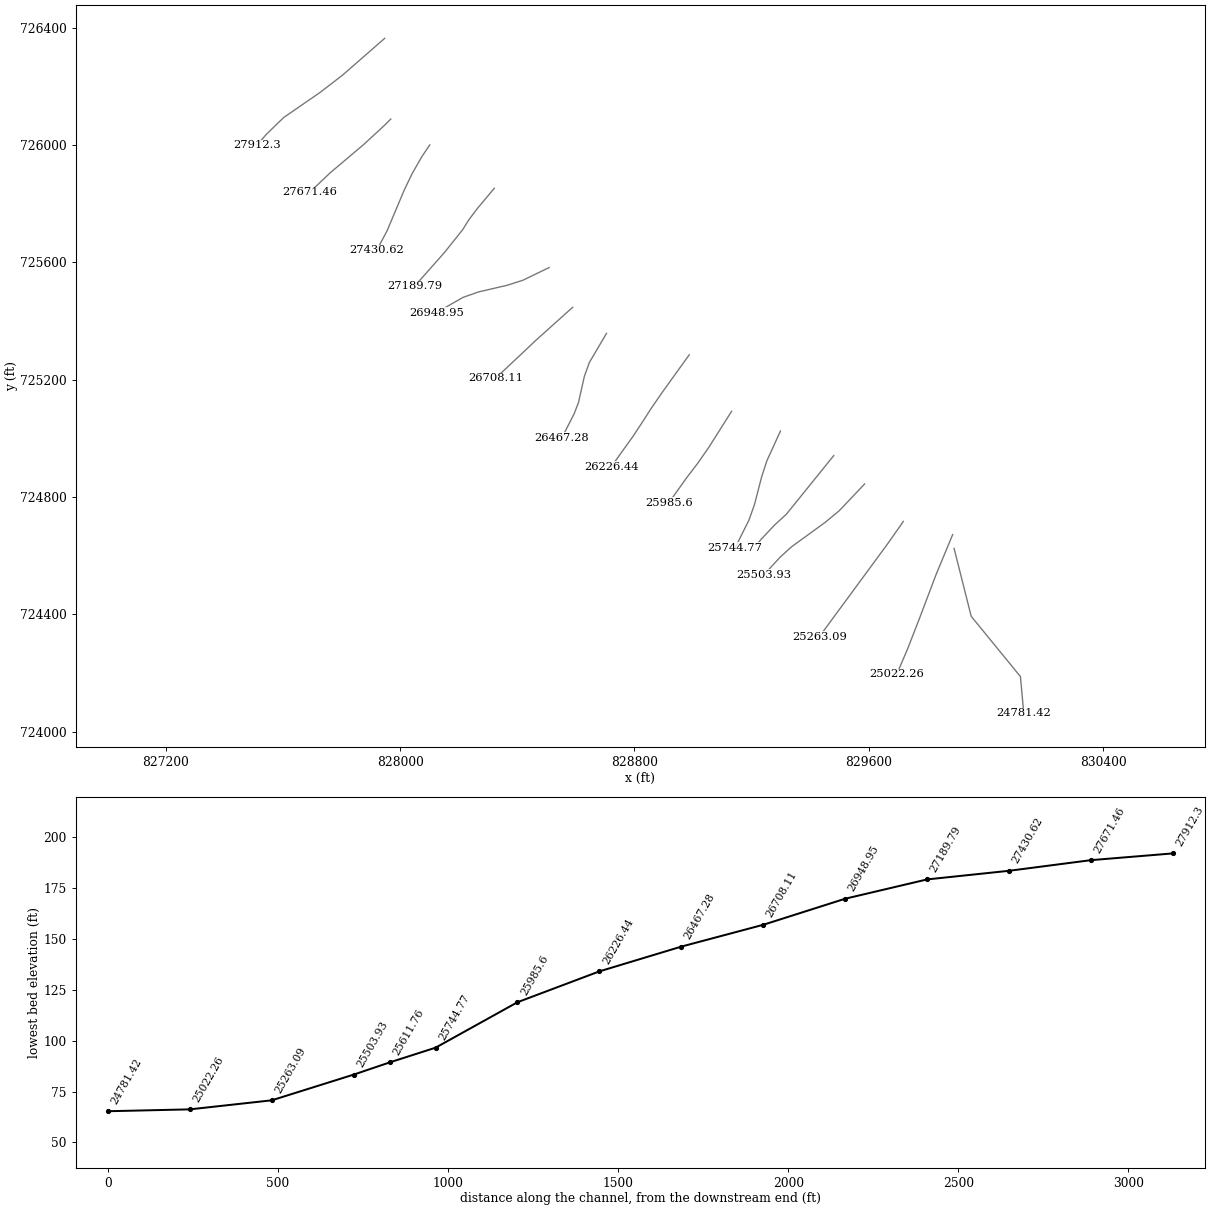
HEC-RAS study 7690_ras.prj: 7690

--- 7690_ras.g01 (geometry) --- (continued)

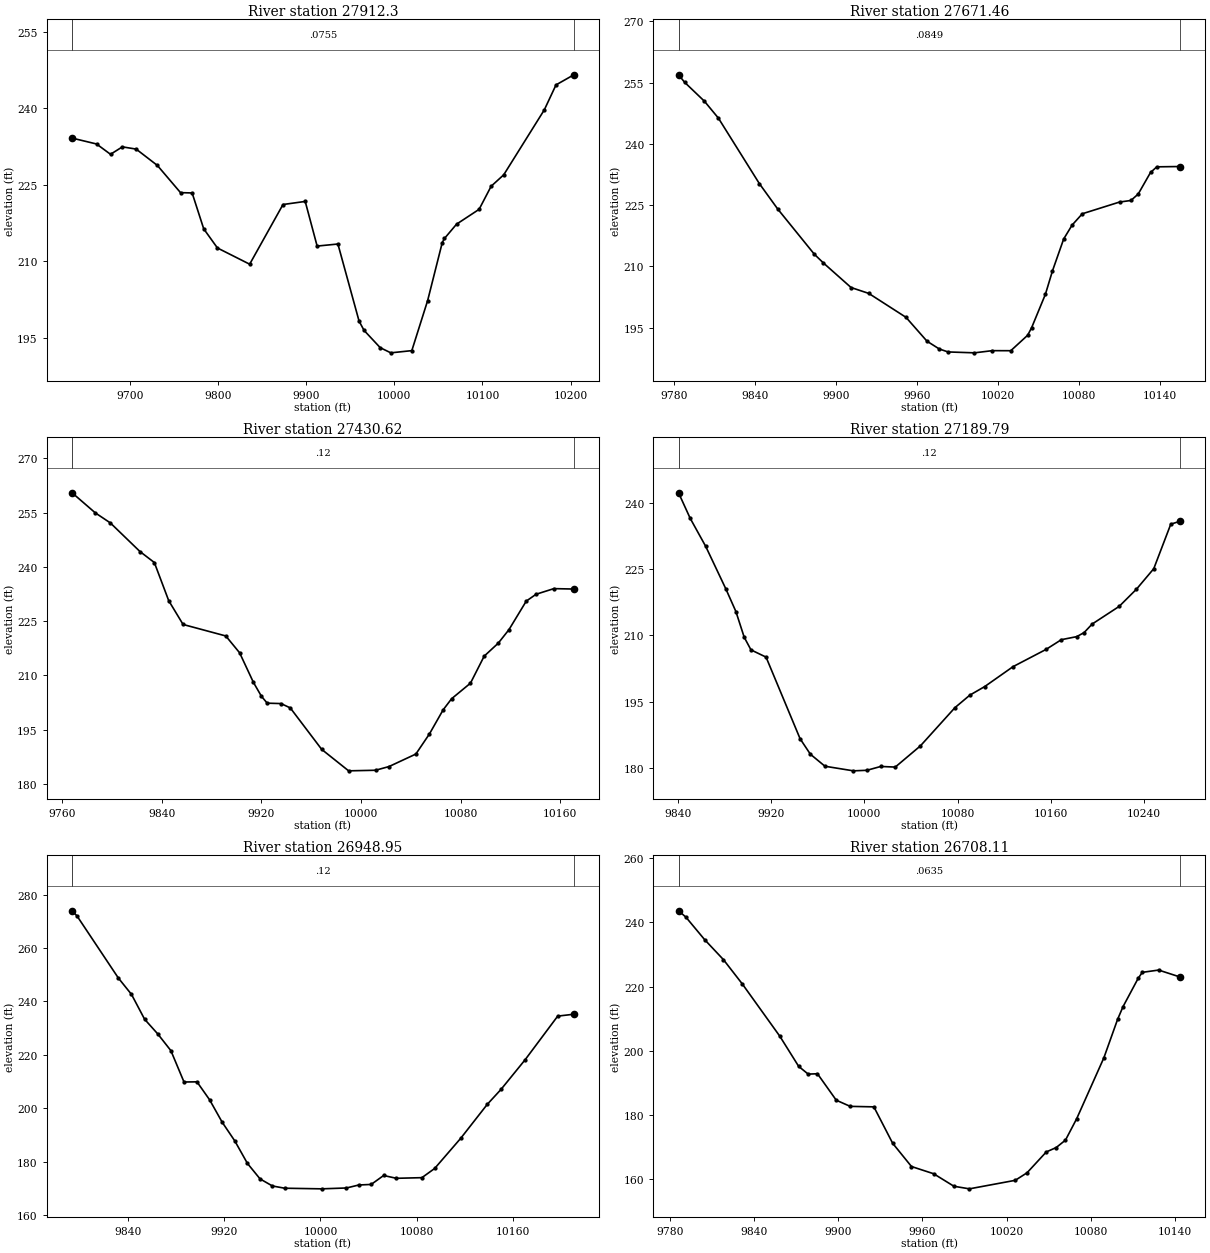
Type RM Length L Ch R = 1 , 27912.3,240.836800,240.836800,240.836800
XS GIS Cut Line= 6
827947.375174125726363.625629629827804.154392677726238.703567831
 827727.00848363726179.420341947827602.476369598726093.645724699
827543.522246534726036.586863089827511.408280152725999.717562257
#Sta/Elev= 30
9634.129234.15099661.907232.99639677.768230.97719691.248232.43369706.877231.9958
9730.927228.80319757.256223.4711 9770.42223.41489783.585216.38619799.134212.6458
9835.736209.46679873.571221.14839898.794 221.7539912.327213.01449935.907213.4186
9959.928198.33189965.575196.5159 9983.95193.1273 9995.96192.119110019.81192.5507
10037.78202.353910054.36213.692910056.87214.503910070.58217.3002 10096.2220.2078
10109.85224.721410124.15226.964110170.23239.680410183.49244.560710203.76246.5416
#Mann= 3 , 0 , 0
9634.129  0.0755       09634.129  0.0755       010203.76  0.0755       0
#XS Ineff= 2 , 0
       09911.991                       0
Bank Sta=9634.129,10203.76
Exp/Cntr=0.3,0.1

Type RM Length L Ch R = 1 ,27671.46,240.836900,240.836900,240.836900
XS GIS Cut Line= 6
827968.149623051726088.559969741827947.313921805726067.671661496
827874.389370817726000.605294788827761.093007168725905.074541306
827702.689556303725849.586561269827692.884608378725839.298628184
#Sta/Elev= 30
9783.554 256.9179788.014255.09259802.707250.44329813.057246.30599843.373230.2725
9856.959224.05039884.131212.95159890.868210.80719911.303204.80449924.389203.3652
9951.972197.50459967.531191.65499976.601189.7545 9983.09189.025910002.69188.8047
10015.82189.338410029.57189.327510042.07193.117410045.01194.9736 10055.2 203.151
10060.44208.890110068.73216.694410074.96220.095710082.53222.871410110.12225.7448
10118.51226.125210123.91227.700910133.03232.9854 10137.7234.3673 10155.1234.4462
#Mann= 3 , 0 , 0
9783.554  0.0849       09783.554  0.0849       0 10155.1  0.0849       0
#XS Ineff= 2 , 0
       0                               0
Bank Sta=9783.554,10155.1
Exp/Cntr=0.3,0.1

Type RM Length L Ch R = 1 ,27430.62,240.836800,240.836800,240.836800
XS GIS Cut Line= 6
828101.366028725726000.404919805828075.175548327725961.906339337
 828040.85700371725902.272321814828014.214930329725846.650536339
827955.241790486725707.131387451827920.298527571725641.474465033
#Sta/Elev= 30
9768.022 260.4769786.654254.92619798.749 252.1429822.553244.22269834.091241.1828
9845.629230.63379857.166224.05269891.452220.8754 9902.54216.22779913.628208.0456
9920.096204.18099924.716202.28459935.804202.17349943.245200.9728 9968.47189.5023
9990.093183.568410011.69183.729310022.49184.749510044.08 188.21310055.02 193.796
10065.99200.441710072.79203.515510087.92207.812910098.95215.293410110.21218.8682
10118.84222.618310132.73230.512510140.59232.404810154.89233.965610170.95233.8503
#Mann= 3 , 0 , 0
9768.022    0.12       09768.022    0.12       010170.95    0.12       0
#XS Ineff= 2 , 0
       0 9943.26                       0
Bank Sta=9768.022,10170.95
Exp/Cntr=0.3,0.1

Type RM Length L Ch R = 1 ,27189.79,240.836800,240.836800,240.836800
XS GIS Cut Line= 6
828321.403009244725852.531793453828263.930944512725783.878219119
828233.580475956725743.673944482828213.715260103725711.547479062
828152.235420331725634.674089147828049.641690827725518.929985521
#Sta/Elev= 30
9840.459242.22219850.477236.43979863.779230.10369881.096220.46929889.703215.3688
9896.837209.54739902.652206.6887  9915.6205.05179944.825186.58859953.655183.0898
9966.184 180.3719990.545179.330810002.18179.453410014.06180.320210026.54180.1807
10048.12184.975210077.76193.618710090.57196.453510103.37198.398410127.63202.8926
10155.88206.777710169.12208.994810182.36 209.68610188.67210.6052 10195.6212.5377
10218.78216.527410233.62220.419810248.47225.054510263.06235.116110271.27235.8081
#Mann= 3 , 0 , 0
9840.459    0.12       09840.459    0.12       010271.27    0.12       0
#XS Ineff= 2 , 0
       0                               0
Bank Sta=9840.459,10271.27
Exp/Cntr=0.3,0.1

Type RM Length L Ch R = 1 ,26948.95,240.836900,240.836900,240.836900
XS GIS Cut Line= 6
 828508.57726038 725582.25272653828418.307914565725538.674155992
828364.873643205725521.738284056828267.405958001725499.122742686
 828214.55143701 725480.49865846828123.830002321725428.722763185
#Sta/Elev= 30
9793.555273.95239797.664272.00979832.039248.77219842.953242.65039853.868233.3338
9864.782227.84959875.696221.59139886.611 209.8429897.385209.90649907.875 203.197
9918.365194.77089928.855187.77379939.346179.35849949.836173.56289960.093170.9194
9970.348170.072610001.11169.841610021.66170.163710031.94171.281710042.22171.4875
10052.58174.837810063.18 173.78710084.39174.024810094.99177.462610116.64 188.755
10138.78201.497710150.17207.076710170.23218.189110197.29234.511510210.72235.2196
#Mann= 3 , 0 , 0
9793.555    0.12       09793.555    0.12       010210.72    0.12       0
#XS Ineff= 2 , 0
       0                               0
Bank Sta=9793.555,10210.72
Exp/Cntr=0.3,0.1

Type RM Length L Ch R = 1 ,26708.11,240.836800,240.836800,240.836800
XS GIS Cut Line= 5
828588.882823458725446.708229591828463.329504397725334.337117406
828431.025246034725303.617781419828429.557169108725302.259565537
828325.208480649725204.414939244
#Sta/Elev= 30
9785.925243.64259791.136241.68379804.557234.64849817.977228.41859831.397220.8752
9858.238204.54659871.658195.17879878.455192.76169885.078 192.8769898.499184.6316
9908.444182.71419925.339182.56099938.759171.2085 9952.18163.97389967.971  161.73
9982.483157.82439993.515157.022310026.23159.675410034.66162.024610048.37168.5087
10055.47  169.8910062.08172.195410070.09178.8774 10089.5197.856510099.33209.8761
10103.21213.819210113.95222.591610116.92224.464310128.57225.174710144.05222.9853
#Mann= 3 , 0 , 0
9785.925  0.0635       09785.925  0.0635       010144.05  0.0635       0
#XS Ineff= 2 , 0
       0                               0
Bank Sta=9785.925,10144.05
Exp/Cntr=0.3,0.1

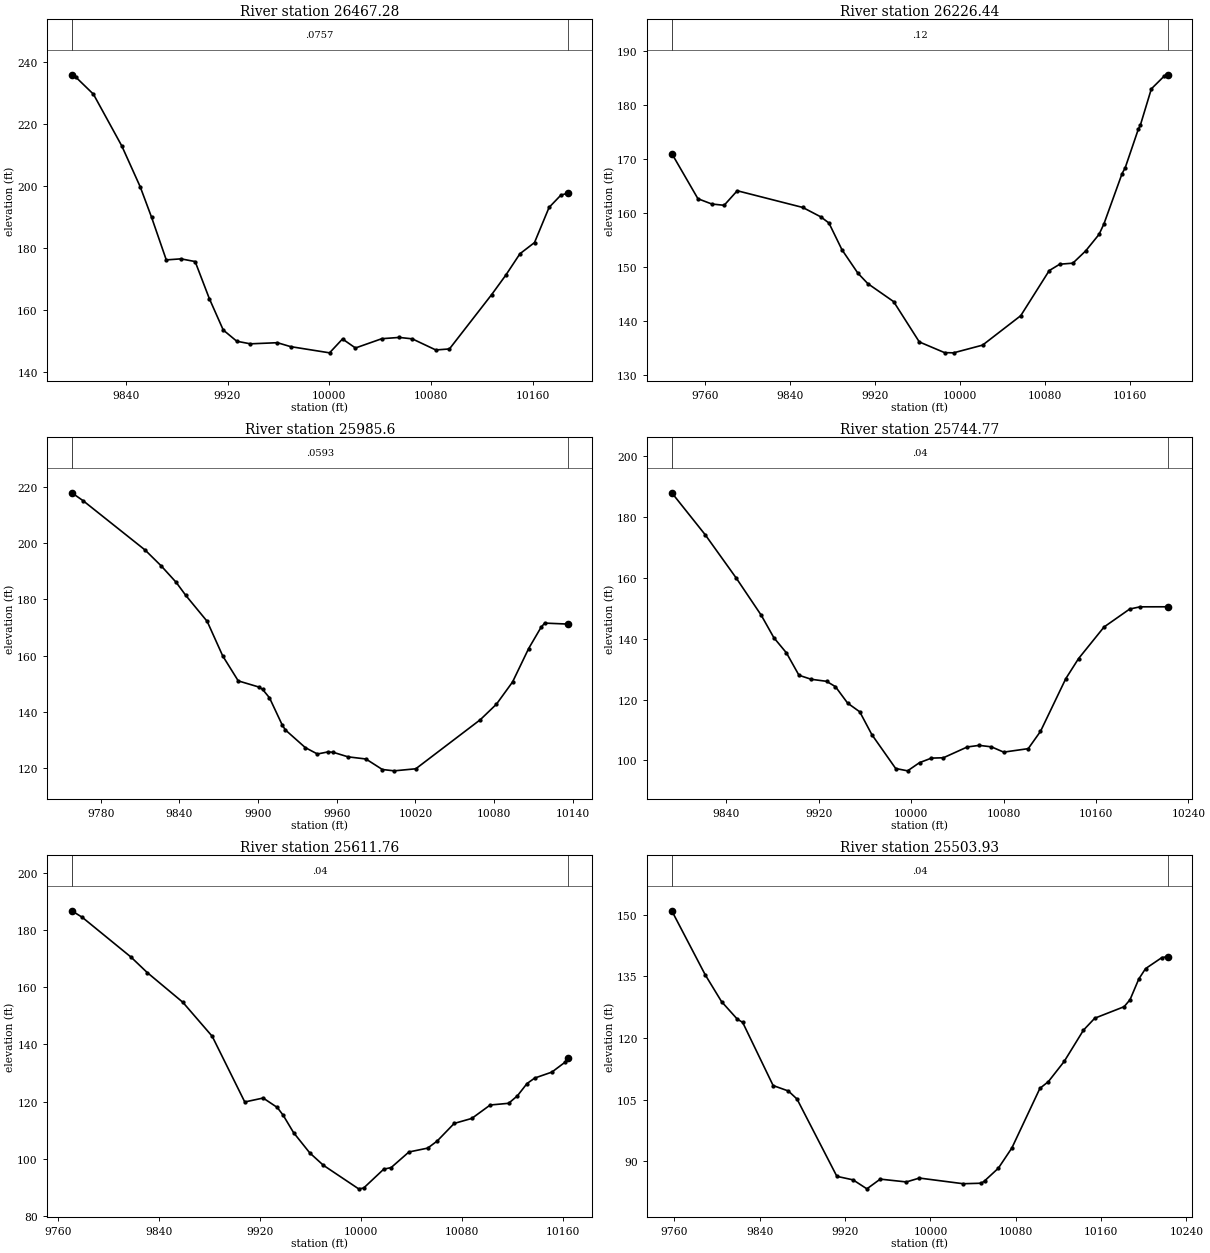
Type RM Length L Ch R = 1 ,26467.28,240.836800,240.836800,240.836800
XS GIS Cut Line= 6
828704.411209265725357.769764137828646.276373896725259.153519115
828629.152227529725212.199933114828608.696225016725121.807026071
828594.063229711725083.955055695828552.363485788725002.216385869
#Sta/Elev= 30
9797.573235.93649800.897235.12279814.601229.66929836.894212.98599851.385199.7974
9860.296189.98589871.839176.25759883.382176.59429894.532175.72189905.681163.7764
 9916.62153.64889927.264 150.0339937.908149.20049959.197 149.5619969.532148.2976
10000.17 146.29510010.34 150.76310020.51147.858410041.22150.849810054.92151.2645
10065.17150.804410083.66147.221210094.39147.5545 10127.6165.095510138.69171.3515
10149.78178.235110161.23181.841310172.68193.175210181.89197.105610187.31197.7787
#Mann= 3 , 0 , 0
9797.573  0.0757       09797.573  0.0757       010187.31  0.0757       0
#XS Ineff= 2 , 0
       0                               0
Bank Sta=9797.573,10187.31
Exp/Cntr=0.3,0.1

Type RM Length L Ch R = 1 ,26226.44,240.836800,240.836800,240.836800
XS GIS Cut Line= 6
828987.017065391725284.976211487828896.772049614725159.714007875
828856.427984553725101.322664875828831.337697201725062.112276929
828795.458516615725007.601888696828719.996630675 724902.52191247
#Sta/Elev= 30
9729.091171.06879753.711 162.6859766.756161.70619778.361161.46919790.686164.1655
9852.311161.0698  9869.4159.31359876.961158.18189889.206153.22719904.185 148.888
9913.515146.95179937.825143.61449961.958136.14449985.711 134.161 9994.17134.1215
10021.49135.5508 10057.4141.009610084.19149.365910094.08150.5492 10106.4150.7401
10118.48153.015410131.02156.066510135.62158.002710152.76167.361910155.64  168.41
10167.95175.540610169.91176.313210180.27183.053410192.58185.462410195.63185.6604
#Mann= 3 , 0 , 0
9729.091    0.12       09729.091    0.12       010195.63    0.12       0
#XS Ineff= 2 , 0
       0                               0
Bank Sta=9729.091,10195.63
Exp/Cntr=0.3,0.1

Type RM Length L Ch R = 1 , 25985.6,240.836900,240.836900,240.836900
XS GIS Cut Line= 6
829131.504052089725092.247008116829053.613361702724969.268324693
 829016.35858475 724915.87258081828978.220315606724865.931137336
828929.138366531724797.286196638828917.715920817724780.519902914
#Sta/Elev= 30
 9757.88217.95389766.459215.15389813.807197.56919826.103191.91059837.481186.0761
9844.792181.43739861.155172.15639872.992159.86839884.829150.98089900.859148.7492
9903.451147.92059908.655 144.9619918.504135.14039920.849133.4832 9935.98127.2184
9945.236124.94379953.456125.70659957.429125.52569968.559123.93299982.194123.1669
9994.736119.424710003.79118.949210020.24119.682610069.42137.152210081.72142.6699
10094.01150.5792 10106.3162.497610115.79170.079810118.55171.552310136.07 171.207
#Mann= 3 , 0 , 0
 9757.88  0.0593       0 9757.88  0.0593       010136.07  0.0593       0
#XS Ineff= 2 , 0
       0                               0
Bank Sta=9757.88,10136.07
Exp/Cntr=0.3,0.1

Type RM Length L Ch R = 1 ,25744.77,133.010000,133.010000,133.010000
XS GIS Cut Line= 6
829298.297055059725025.131162796829251.819090063 724923.24529126
829233.939920771724868.420226687829209.377517224724773.630493305
829190.455885914  724720.6350724829143.215029756724626.366737673
#Sta/Elev= 30
9792.675187.95839821.689174.14019848.495159.93949870.227 147.6759881.093140.3292
9891.959135.35849902.825127.99799913.404126.67939926.726126.00699934.441124.2426
9944.959118.84779955.478115.97989965.928 108.4969986.56697.360159996.886 96.5938
 10007.299.2815110017.54 100.77710027.88100.889210048.56104.4374 10058.9104.9628
10069.48104.4786 10080.1102.740910101.34103.883710111.96109.555110133.85126.8686
 10144.9133.464310166.98143.849810189.21149.755210198.17150.483710222.11150.4982
#Mann= 3 , 0 , 0
9792.675    0.04       09792.675    0.04       010222.11    0.04       0
#XS Ineff= 2 , 0
       0                10072.79       0
Bank Sta=9792.675,10222.11
Exp/Cntr=0.3,0.1

Type RM Length L Ch R = 1 ,25611.76,107.826800,107.826800,107.826800
XS GIS Cut Line= 5
829480.251387551724941.364025762829318.075990432724741.018861628
829278.893006611724705.294298001829234.379050855724658.212014771
829223.605207389  724645.4299529
#Sta/Elev= 30
9771.127186.74439779.473184.43979817.911170.56779830.777165.14369858.942154.7504
 9882.24142.81679907.971119.84979922.517121.23019933.703117.92859938.411115.1718
9946.568109.13119959.434102.01299970.19897.691179998.03189.4589810001.9989.72752
10017.8896.3309310023.7696.8984810037.82102.349510052.66103.708910060.11106.1573
10073.64112.341810087.57114.096310102.13118.790710116.69119.3856 10123.6121.9834
10131.24126.293610137.36 128.224 10150.9130.298810161.25133.732310163.42135.1204
#Mann= 3 , 0 , 0
9771.127    0.04       09771.127    0.04       010163.42    0.04       0
#XS Ineff= 2 , 0
       0                               0
Bank Sta=9771.127,10163.42
Exp/Cntr=0.3,0.1

Type RM Length L Ch R = 1 ,25503.93,240.836800,240.836800,240.836800
XS GIS Cut Line= 6
829585.551817712724844.615863081829498.976034565724753.406926866
829451.439121815724714.123264537829335.924372711724630.268073819
829296.741330496724594.543437873829241.453451491724534.678974524
#Sta/Elev= 30
9757.541150.91979788.944135.33689804.223128.83669818.946 124.5919823.989123.8015
9852.557108.44689866.841107.12749874.964105.16249912.29686.387699927.47685.52754
9940.44983.348659952.94985.709839977.42585.023349989.66485.9677910030.7484.58996
10047.7884.7157210050.9185.3152310063.6288.3531410076.3393.2789110102.64107.7763
10110.52109.390910125.36 114.29810143.42 121.90210154.02124.813210181.54127.6087
10187.09129.3075 10195.3134.338710201.64136.863410216.89139.538110222.39139.8035
#Mann= 3 , 0 , 0
9757.541    0.04       09757.541    0.04       010222.39    0.04       0
#XS Ineff= 2 , 0
       0                               0
Bank Sta=9757.541,10222.39
Exp/Cntr=0.3,0.1

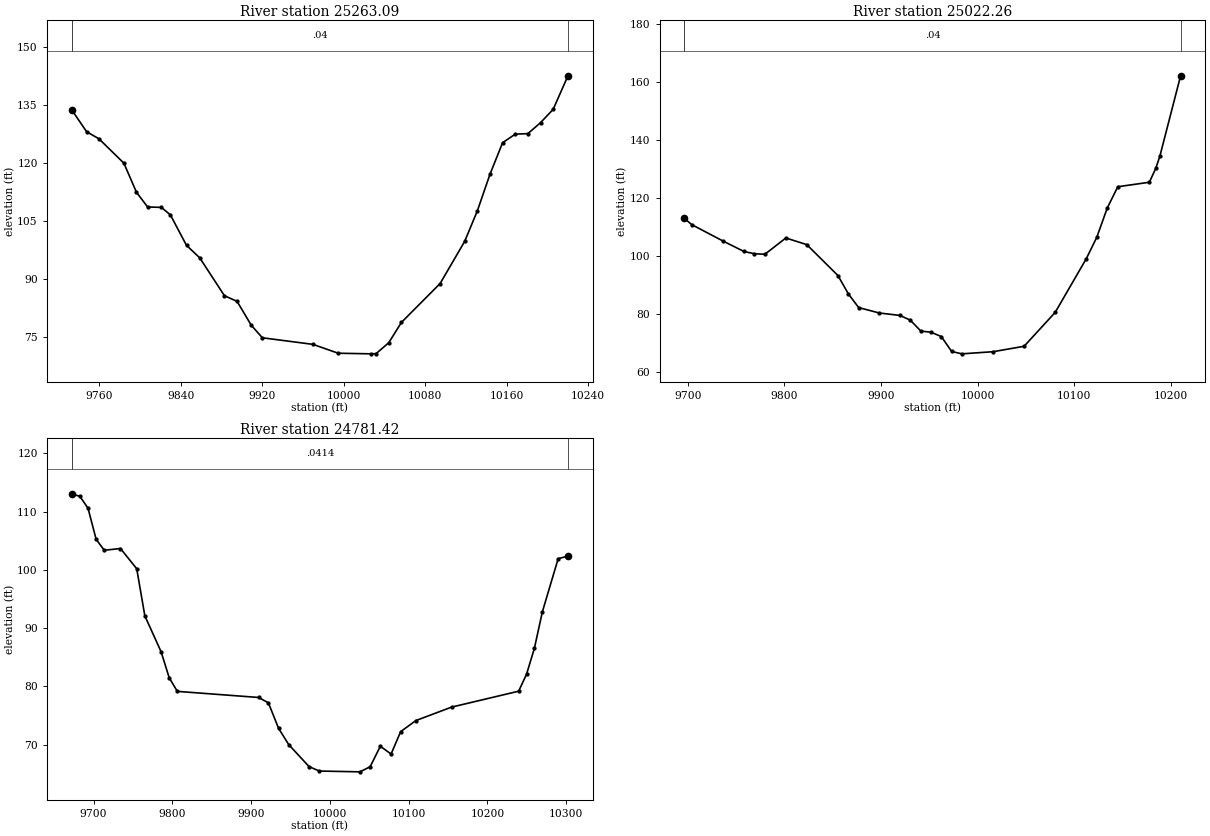
Type RM Length L Ch R = 1 ,25263.09,240.836900,240.836900,240.836900
XS GIS Cut Line= 6
829717.551968882724717.123774797829707.486310101724701.916201969
829662.098418137724637.788667719829561.749738038724501.449906891
829560.569575479724499.835219254829430.520290962724323.287886269
#Sta/Elev= 30
9732.911133.8151 9747.45128.18069759.622126.33949784.124120.02299796.375112.5421
9807.381108.70069820.878108.60049829.713106.67369845.59298.772879858.55895.55843
9882.84285.753779895.259 84.28739909.16778.123279920.09274.866959969.75973.16576
9994.59270.8689510027.2570.7122610031.8570.7685110044.2773.5954210056.6978.84197
 10094.788.9037810118.7999.7900710131.21107.664410143.63117.139110156.05125.3256
10168.47127.542110180.89127.682510193.31130.504610205.73133.965910220.28142.6459
#Mann= 3 , 0 , 0
9732.911    0.04       09732.911    0.04       010220.28    0.04       0
#XS Ineff= 2 , 0
       0                               0
Bank Sta=9732.911,10220.28
Exp/Cntr=0.3,0.1

Type RM Length L Ch R = 1 ,25022.26,240.836800,240.836800,240.836800
XS GIS Cut Line= 6
829886.086303034724671.997919028829829.100704941724534.746961743
829773.837400837724388.974979237 829732.24301262724282.135606334
829697.620637365  724201.6954677829694.621397244724195.368736302
#Sta/Elev= 30
9696.493112.9927 9704.07110.85969736.553105.17429758.209101.58419769.036100.8056
9779.864100.63939801.519106.24939823.175103.95519855.528 93.25099866.22386.95586
9876.91882.232669898.30880.362169919.69879.519379930.39377.878579941.27774.11918
9951.78273.737169962.47772.232839973.17267.078139983.867 66.2686   1001667.00304
10048.19 68.879910080.3880.5784910112.5899.1001810123.42106.462710134.31 116.606
10145.19123.931910177.85125.479310184.56130.302810188.74134.461110210.23162.2209
#Mann= 3 , 0 , 0
9696.493    0.04       09696.493    0.04       010210.23    0.04       0
#XS Ineff= 2 , 0
       0 9926.47                       0
Bank Sta=9696.493,10210.23
Exp/Cntr=0.3,0.1

Type RM Length L Ch R = 1 ,24781.42,139.099200,139.099200,139.099200
XS GIS Cut Line= 4
829890.989481978724624.955686414 829949.46510761724393.366240579
830117.445354443724188.161271491830128.865756125724062.625613528
#Sta/Elev= 30
9672.295113.04279682.564112.59159692.877110.58159703.191105.23899713.505103.3541
9734.133103.6513 9754.76100.18719765.07492.096049785.70285.947939796.01681.47422
 9806.3379.146989909.46878.103159921.96577.183439934.888 72.80929947.81270.01101
9973.65866.237849986.58165.4823610038.2765.34531 10051.266.2225710064.1269.73548
10077.7668.3998610089.9772.2496810109.3474.1476210154.5876.4473510239.7779.17907
10249.8182.0967510259.7386.5261410269.8992.7969610289.97101.9182 10302.4102.3417
#Mann= 3 , 0 , 0
9672.295  0.0414       09672.295  0.0414       0 10302.4  0.0414       0
#XS Ineff= 2 , 0
       09920.336        10096.66       0
Bank Sta=9672.295,10302.4
Exp/Cntr=0.3,0.1