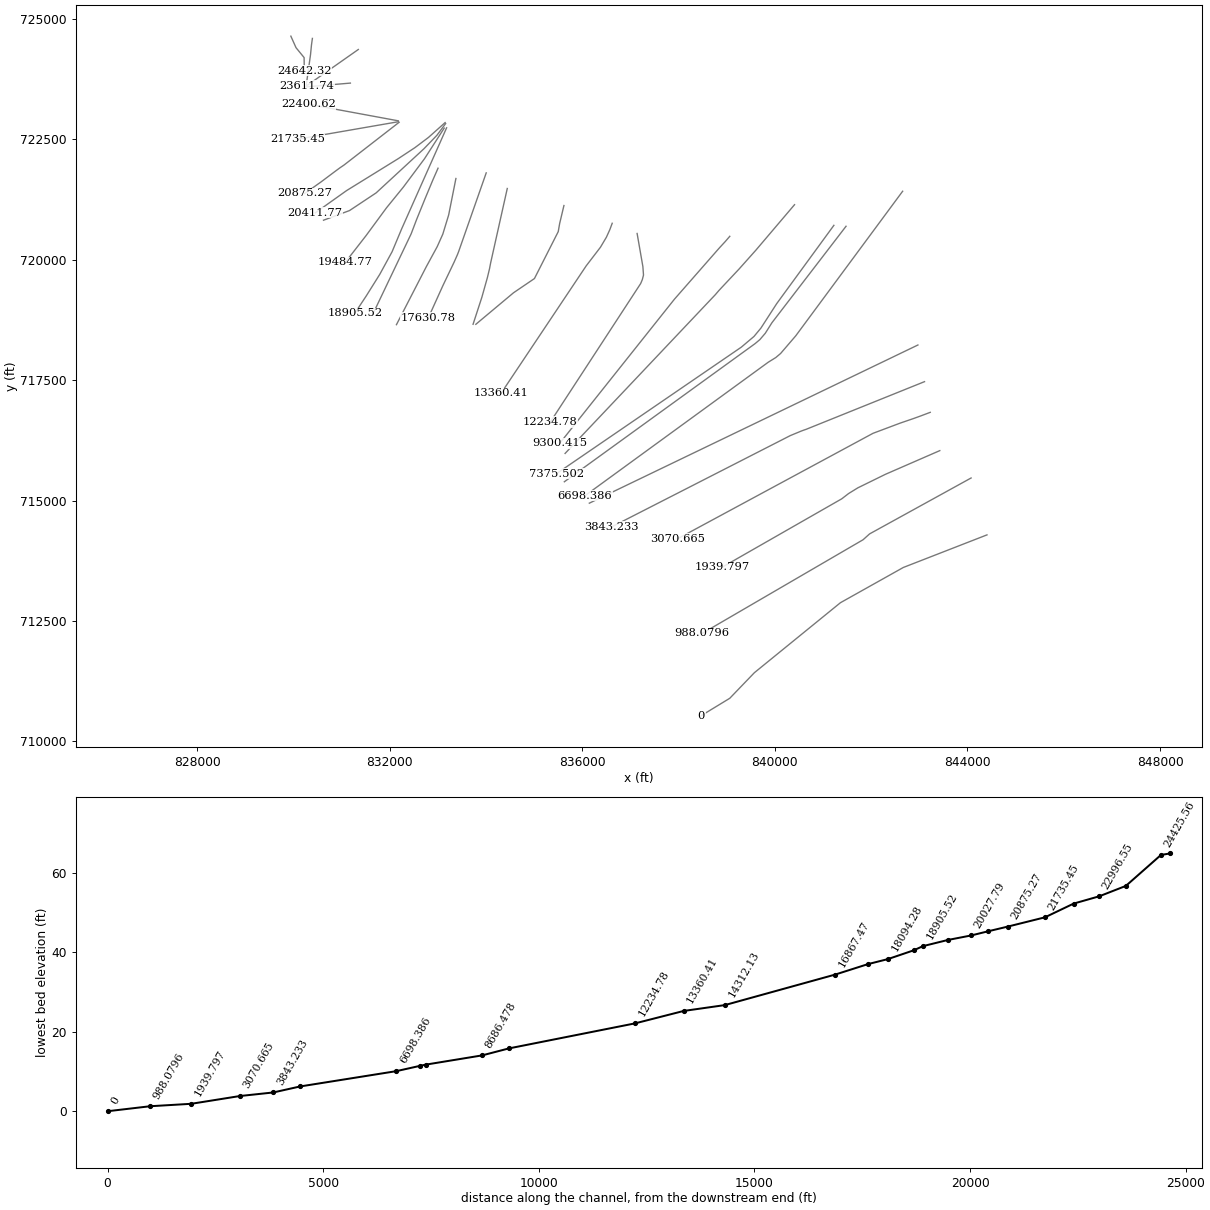
HEC-RAS study 7690_ras.prj: 7690

--- 7690_ras.g01 (geometry) --- (continued)

Type RM Length L Ch R = 3 ,24696.07,,,
BEGIN DESCRIPTION:
END DESCRIPTION:
Bridge Culvert--1,0,-1,-1, 0
Deck Dist Width WeirC Skew NumUp NumDn MinLoCord MaxHiCord MaxSubmerge Is_Ogee
56.049600,27.000000,2.6,0, 26, 26, , , 0.95, 0, 0,0,,
 9849.47 9855.04 9859.85 9868.57 9874.70 9882.10 9889.54 9895.64 9904.38 9905.96
 9950.53 9950.5310063.5310063.5310080.0210083.9710084.0310096.1710101.5010108.36
10118.9810120.5610132.7510136.4510144.9510146.24
   78.76   78.89   79.10   79.61   80.00   80.54   81.21   81.77   82.65   82.77
   82.40   82.40   81.47   81.47   81.33   80.91   80.91   79.60   79.04   78.31
   77.21   77.06   76.00   75.72   75.01   74.91
 -921.24 -921.11 -920.90 -920.39 -920.00 -919.46 -918.79 -918.23 -917.35 -917.23
 -917.60   75.40   74.47 -918.53 -918.67 -919.09 -919.09 -920.40 -920.96 -921.69
 -922.79 -922.94 -924.00 -924.28 -924.99 -925.09
 9849.47 9855.04 9859.85 9868.57 9874.70 9882.10 9889.54 9895.64 9904.38 9905.96
 9931.26 9931.2610044.2610044.2610080.0210083.9710084.0310096.1710101.5010108.36
10118.9810120.5610132.7510136.4510144.9510146.24
   78.76   78.89   79.10   79.61   80.00   80.54   81.21   81.77   82.65   82.77
   82.56   82.56   81.63   81.63   81.33   80.91   80.91   79.60   79.04   78.31
   77.21   77.06   76.00   75.72   75.01   74.91
 -921.24 -921.11 -920.90 -920.39 -920.00 -919.46 -918.79 -918.23 -917.35 -917.23
 -917.44   75.56   74.63 -918.37 -918.67 -919.09 -919.09 -920.40 -920.96 -921.69
 -922.79 -922.94 -924.00 -924.28 -924.99 -925.09
BR Coef=-1 , 0 , 0 ,, 0 ,,,0.8,0,1,0,
WSPro=,,,, 1 ,,,, 0 ,,,, 0 ,,,,-1 ,-1 ,-1 , 0 , 0 , 0 , 0 , 0
BC Design=,, 0 ,, 0 ,,,,,,

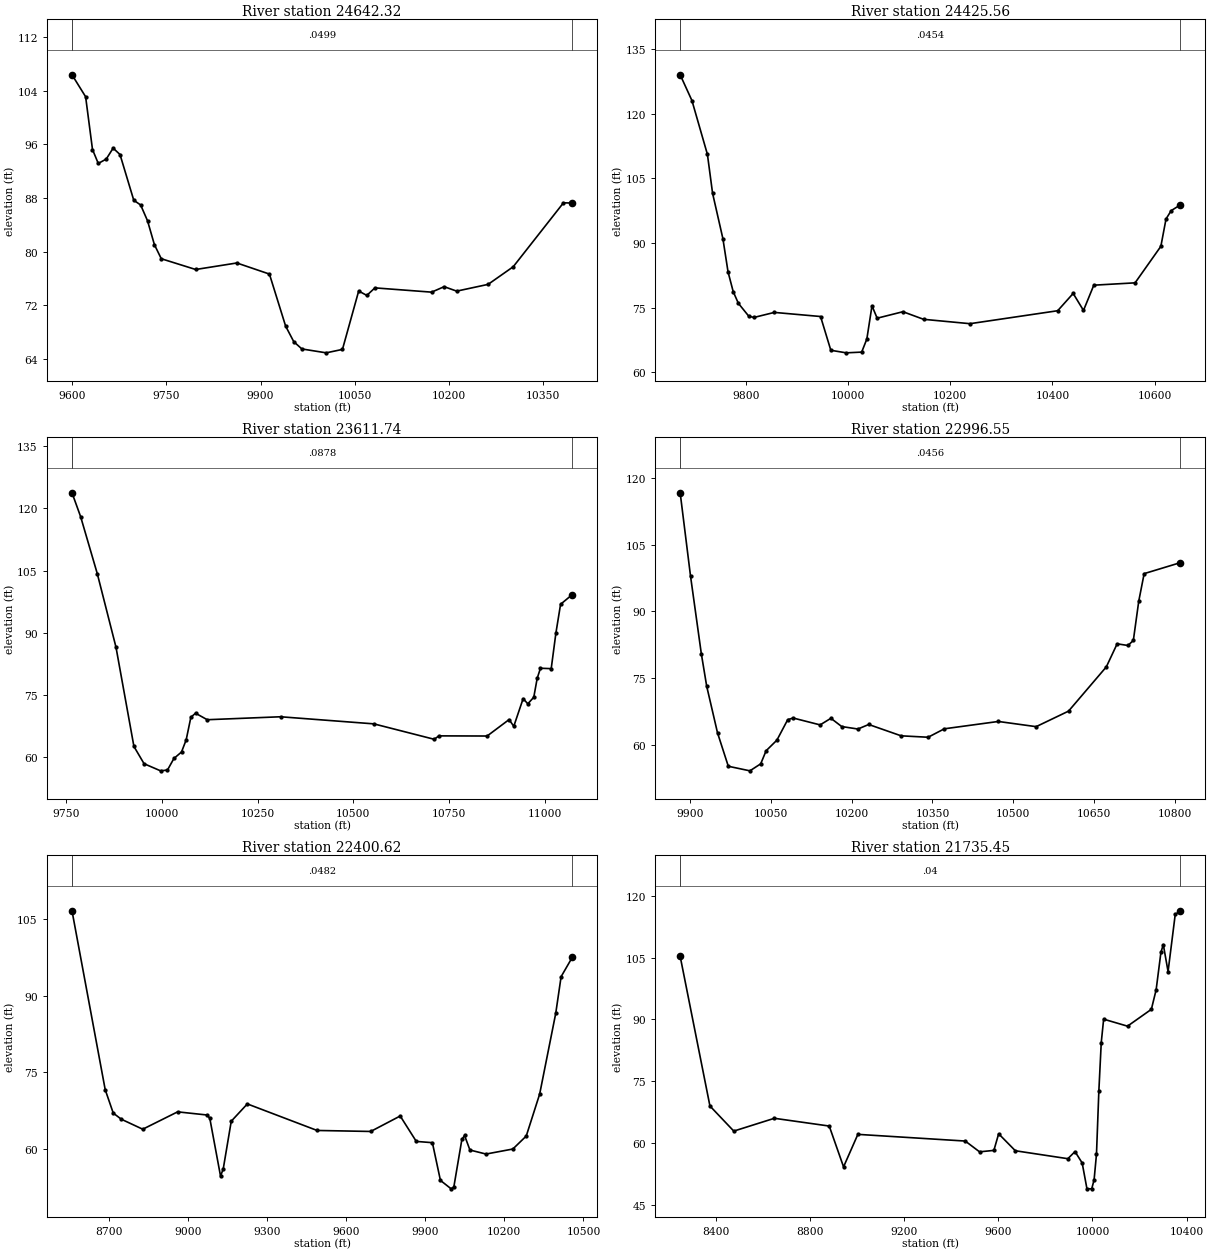
Type RM Length L Ch R = 1 ,24642.32,216.754200,216.754200,216.754200
XS GIS Cut Line= 4
829947.911229966724644.808832323830055.127867907724405.145318271
830223.108425324724199.940664903830226.539831627723931.035445214
#Sta/Elev= 30
9599.731106.36629621.432103.09429632.38795.229549641.57893.149489654.297 93.8072
9665.25295.433559676.20794.480239698.11787.665699709.07286.959289720.02784.60884
9730.98281.048579741.93778.950949796.71377.347559862.28478.319149914.16576.66653
9940.01168.898439952.93466.589129965.85865.5052910004.6364.9272210030.4765.44053
10056.3274.1424110069.2473.4842410082.1774.6085710172.4273.9724210192.4274.78672
10212.42 74.123810262.4375.1301410302.4377.7583410382.4487.28577 10396.487.25096
#Mann= 3 , 0 , 0
9599.731  0.0499       09599.731  0.0499       0 10396.4  0.0499       0
#XS Ineff= 2 , 0
       09907.636        10067.53       0
Bank Sta=9599.731,10396.4
Exp/Cntr=0.3,0.1

Type RM Length L Ch R = 1 ,24425.56,813.827700,813.827700,813.827700
XS GIS Cut Line= 5
830395.171164552724597.825369468830376.562387707724464.901832652
830356.791073527724265.641648862830356.589778265724263.651804514
830267.676670754723627.113532749
#Sta/Elev= 30
9671.488129.04669694.536123.06369724.829110.58179734.926101.55679755.121 91.0334
9765.21983.311649775.31678.733159785.41476.023729805.60973.061739815.65872.73935
9855.85573.914389946.29772.962629966.39565.128059996.54264.5347510026.7864.70426
10036.88 67.732410046.9775.4429210057.07 72.572110107.5674.0765110147.9472.31238
10238.8271.2983610410.4774.3058210440.7678.3159310460.9574.3736410481.1580.23236
10561.9380.7738810612.41 89.245410622.5195.59621 10632.697.5242410650.6698.86815
#Mann= 3 , 0 , 0
9671.488  0.0454       09671.488  0.0454       010650.66  0.0454       0
#XS Ineff= 2 , 0
       0                10174.21       0
Bank Sta=9671.488,10650.66
Exp/Cntr=0.3,0.1

Type RM Length L Ch R = 1 ,23611.74,615.184100,615.184100,615.184100
XS GIS Cut Line= 2
831349.023145529724367.931669893830280.089809758723617.298507712
#Sta/Elev= 30
9765.251123.73389787.754117.99279831.264104.25419880.14186.52543 9926.9662.61468
9953.45858.450989996.56456.7372910014.5556.9336210031.3759.7131210051.2161.27445
10063.4364.2102610075.6569.6512810087.8770.6210610118.3769.0529910309.78 69.7657
10553.3968.0562210711.0664.3372310723.2865.1622510849.2165.1264810906.5769.08886
10918.8167.4656210943.2274.1356410955.4472.8852210971.0174.4680610979.8879.00894
10988.41 81.455211016.5481.3612611028.7689.9225811040.9896.8617711071.4299.19565
#Mann= 3 , 0 , 0
9765.251  0.0878       09765.251  0.0878       011071.42  0.0878       0
#XS Ineff= 2 , 0
       0                10775.57       0
Bank Sta=9765.251,11071.42
Exp/Cntr=0.3,0.1

Type RM Length L Ch R = 1 ,22996.55,595.935300,595.935300,595.935300
XS GIS Cut Line= 2
831184.143660326723669.844871669830257.866544246723590.973693436
#Sta/Elev= 30
9881.209116.66089900.42297.964479920.49580.494619930.53173.144259950.60362.68099
9970.676 55.156110010.8254.1274110030.8955.7049510040.9358.64347   1006161.03327
10081.0765.6305910091.11 66.008710141.2964.4594310161.3665.9456410181.4464.08656
10211.5463.5316410231.62 64.550810291.8362.0019410342.0161.6832710372.1263.58052
10472.4865.2308410542.7464.0630810602.9667.5545810673.2177.5151110693.2882.69379
10713.3582.3162310723.3983.4569710733.4392.2819310743.4698.4765610810.84 100.951
#Mann= 3 , 0 , 0
9881.209  0.0456       09881.209  0.0456       010810.84  0.0456       0
#XS Ineff= 2 , 0
       0                10521.87       0
Bank Sta=9881.209,10810.84
Exp/Cntr=0.3,0.1

Type RM Length L Ch R = 1 ,22400.62,665.165400,665.165400,665.165400
XS GIS Cut Line= 2
832178.864545017722886.306634532830313.521224821723230.921644596
#Sta/Elev= 30
8560.744106.53238686.70571.622878717.21267.05658 8747.7265.861878829.07463.90973
8961.27467.299739073.13566.683419083.30466.041279123.98154.77548 9134.1556.12729
9164.65865.473459225.673 68.84599490.07363.668679693.45863.473029805.31966.48949
9866.33461.53063 9927.3561.284829957.85753.926149998.534 52.2775 10008.752.64362
10039.2161.9223610049.3862.6892710069.7259.8502210130.7359.0660510232.4360.04618
10283.2762.5777410334.1270.7609510395.1386.5304610415.4793.6751110457.6597.43638
#Mann= 3 , 0 , 0
8560.744  0.0482       08560.744  0.0482       010457.65  0.0482       0
#XS Ineff= 2 , 0
       09577.742                       0
Bank Sta=8560.744,10457.65
Exp/Cntr=0.3,0.1

Type RM Length L Ch R = 1 ,21735.45,860.186100,860.186100,860.186100
XS GIS Cut Line= 2
832179.742526946722867.431599217830083.301740223722503.813973119
#Sta/Elev= 30
8246.199105.35858372.80468.966118474.29762.858288646.83565.972928880.26964.08693
8941.16554.161659002.06162.064949458.779 60.43999519.67557.817339580.57158.16814
9600.86962.204399671.91458.077939895.19956.148639925.64757.876689956.09555.11704
9976.39448.851759996.69248.8198110006.8451.0048310016.9957.2552810027.14 72.7047
10037.2984.3975810047.4490.0759910148.9388.3729210250.4292.4679910270.7297.20876
10291.02106.295310301.17108.219410321.47101.651510351.92115.533310373.94116.4287
#Mann= 3 , 0 , 0
8246.199    0.04       08246.199    0.04       010373.94    0.04       0
#XS Ineff= 2 , 0
       09163.855                       0
Bank Sta=8246.199,10373.94
Exp/Cntr=0.3,0.1

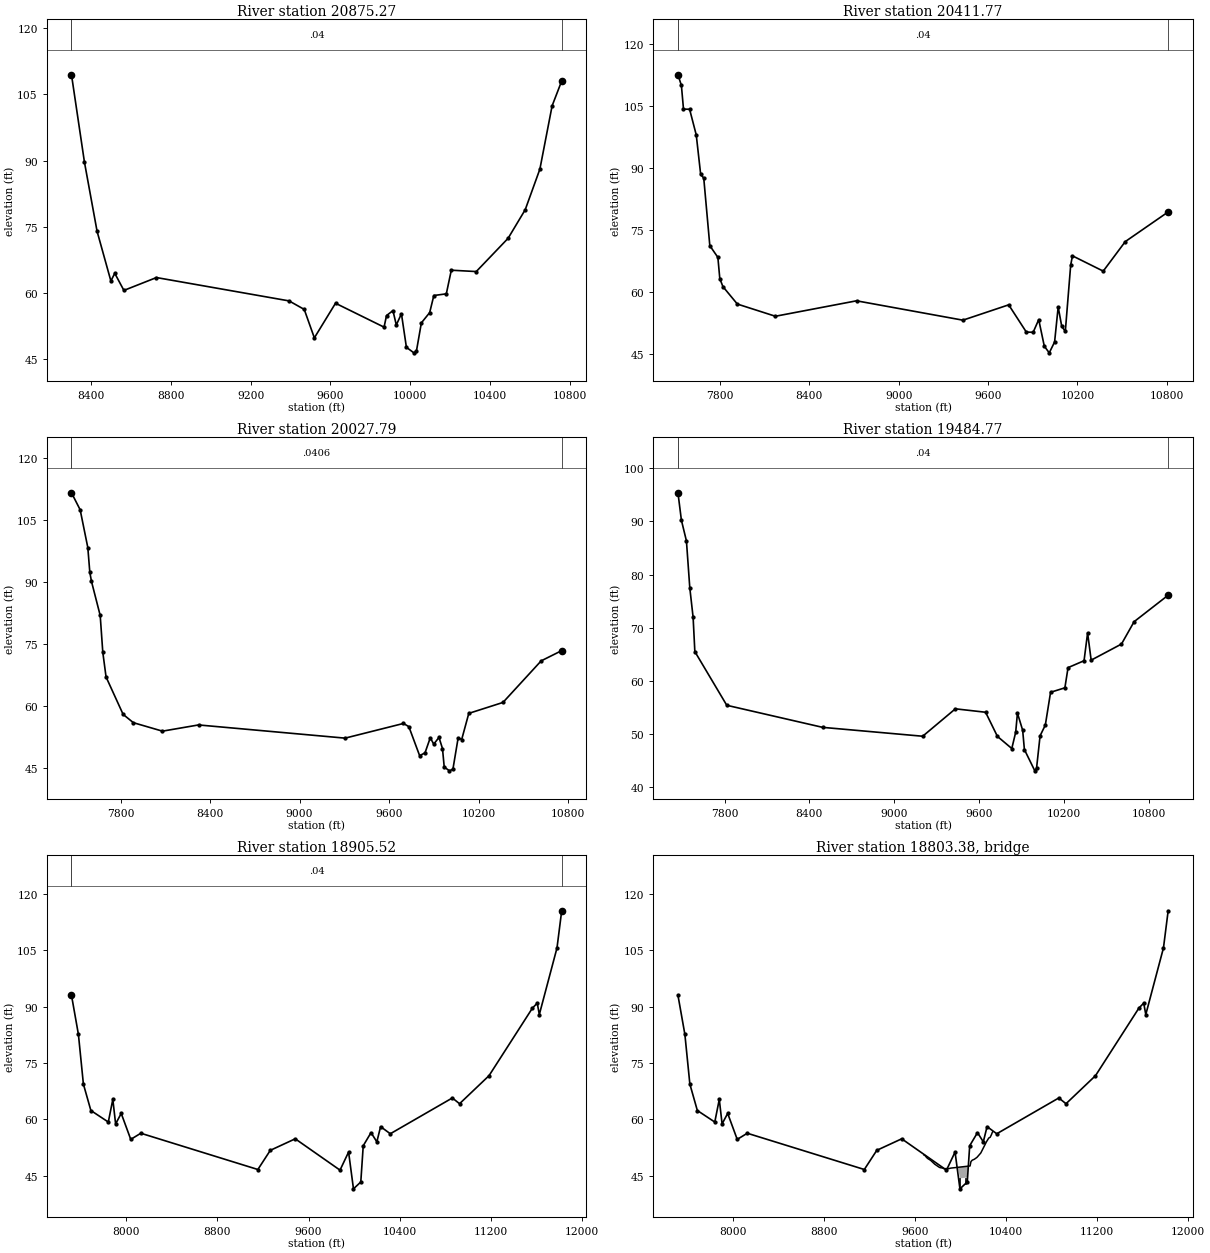
Type RM Length L Ch R = 1 ,20875.27,463.498100,463.498100,463.498100
XS GIS Cut Line= 6
832196.289429795722855.986747437831051.765862186721967.818092652
830962.523012192721907.099436954830850.107617243721823.821511666
830576.263692285721618.375979004830235.803420984721377.361527891
#Sta/Elev= 30
8302.443109.42118367.36489.646958430.65373.995828499.78762.753028519.25764.48984
8565.03260.617758728.14563.527639392.64658.243959468.59356.316289519.22449.87867
9625.26557.713729868.461 52.30359880.90654.928539913.02356.040659929.82352.79857
9955.57655.330419980.46647.73505 10017.946.48882 10030.446.81186 10055.453.26945
   1009755.5926110117.9159.4642210180.41  59.84210205.4165.1918410330.4264.88429
10489.9272.4109410575.6878.8759210649.1988.0679410710.45102.387810758.48108.0192
#Mann= 3 , 0 , 0
8302.443    0.04       08302.443    0.04       010758.48    0.04       0
#XS Ineff= 2 , 0
       09256.214                       0
Bank Sta=8302.443,10758.48
Exp/Cntr=0.3,0.1

Type RM Length L Ch R = 1 ,20411.77,383.974300,383.974300,383.974300
XS GIS Cut Line= 6
833151.326517211 722849.37415663832806.071230453722541.554788693
832526.540313671722330.736267501832180.625621121722102.136492918
831104.275959419 721436.73603621830454.906157561720974.432601226
#Sta/Elev= 30
7518.675112.64997541.745110.07727555.875104.32227596.832 104.3037641.52198.07139
7671.10188.526317691.84187.617137732.55971.249757786.58968.417627799.66963.23753
7820.92361.306997917.39457.101358172.72454.147848717.20357.891079431.19553.19962
9738.64956.914299856.95550.320319902.78950.262079940.21853.335039977.64746.89811
10010.8145.28574 10046.847.9196610070.7956.4042510094.7851.6862110118.7850.48664
10154.7766.5534910166.7768.7842710373.1765.0822110521.1172.2345910809.0379.42145
#Mann= 3 , 0 , 0
7518.675    0.04       07518.675    0.04       010809.03    0.04       0
#XS Ineff= 2 , 0
       0 8971.38                       0
Bank Sta=7518.675,10809.03
Exp/Cntr=0.3,0.1

Type RM Length L Ch R = 1 ,20027.79,543.021800,543.021800,543.021800
XS GIS Cut Line= 6
 833162.50570379722829.120151734832978.962166332722583.104248532
832711.572197704722305.876883774831719.005664116721389.756453088
831165.764814171721022.247852996830625.944162772720822.061832873
#Sta/Elev= 30
7471.658111.54787529.779107.42817581.04298.282787594.43292.308417605.48490.11255
7664.01681.853187681.41272.941497703.25366.976167817.61957.91969 7886.4155.90905
8081.16553.862018322.59855.366449304.64652.172479695.60355.725319731.77254.95459
9803.94947.935399840.03748.610619875.22452.261119898.60150.721889933.666 52.3459
9957.043 49.66339968.73245.1925510003.78 44.259410027.13 44.676110062.1452.26268
10085.75 51.837910133.3358.1649610362.4160.8119610618.2170.8701310755.7573.34995
#Mann= 3 , 0 , 0
7471.658  0.0406       07471.658  0.0406       010755.75  0.0406       0
#XS Ineff= 2 , 0
       08784.453                       0
Bank Sta=7471.658,10755.75
Exp/Cntr=0.3,0.1

Type RM Length L Ch R = 1 ,19484.77,579.252800,579.252800,579.252800
XS GIS Cut Line= 6
833133.038752958722735.471471413832723.574627726722099.061534286
832283.086131642721508.418812729831934.561911436721079.931374606
831513.097562523720506.663050041831077.111246878719945.880551988
#Sta/Elev= 30
7470.08895.37214 7494.4390.224417530.103 86.31377553.88577.495967577.35371.95485
7589.55865.528237815.48755.433298493.87951.284979201.38349.617169432.78754.77073
9646.48154.12602 9730.0549.587129831.79247.308819859.36450.379729871.67553.96302
9908.60950.74734 9920.9247.109929994.78743.1143810007.1543.6667610031.8749.69976
10068.9551.7137410106.0357.8771710207.3358.7169110229.6762.5104610342.8763.80829
10368.0269.0394910393.1863.9151310607.7166.9434810696.9271.1431310937.9376.12376
#Mann= 3 , 0 , 0
7470.088    0.04       07470.088    0.04       010937.93    0.04       0
#XS Ineff= 2 , 0
       0 8616.97                       0
Bank Sta=7470.088,10937.93
Exp/Cntr=0.3,0.1

Type RM Length L Ch R = 1 ,18905.52,211.279200,211.279200,211.279200
XS GIS Cut Line= 6
833182.570482824722740.533835849832249.807404172720644.209059212
832050.458350768720167.985466191 831794.99748098719698.938891065
831515.612938378719252.572354165831276.365404772718890.759532922
#Sta/Elev= 30
7517.71993.004037578.50282.615037622.28369.397287687.95562.375937841.18859.30813
7880.72465.329747905.322 58.8189 7954.5261.601768038.20254.701878126.71156.33148
9154.61646.694879264.06951.791749482.97454.852929876.18646.524859951.56351.33229
  9994.441.5555910058.7143.3779910080.1653.0119710148.64 56.499210199.6654.04761
10232.7358.0894710317.8456.1947610862.88 65.7122 10926.164.1781411184.99  71.631
11566.27 89.597211608.6190.9117111626.7787.89309   11782105.590811823.27115.4615
#Mann= 3 , 0 , 0
7517.719    0.04       07517.719    0.04       011823.27    0.04       0
#XS Ineff= 2 , 0
       08660.625        10100.73       0
Bank Sta=7517.719,11823.27
Exp/Cntr=0.3,0.1

Type RM Length L Ch R = 3 ,18803.38,,,
BEGIN DESCRIPTION:
END DESCRIPTION:
Bridge Culvert--1,0,-1,-1, 0
Deck Dist Width WeirC Skew NumUp NumDn MinLoCord MaxHiCord MaxSubmerge Is_Ogee
94.639600,22.000000,2.6,0, 28, 29, , , 0.95, 0, 0,0,,
 9678.30 9686.18 9701.72 9713.53 9737.14 9772.56 9807.97 9819.78 9843.39 9855.19
 9878.80 9890.61 9914.38 9942.03 9942.0310083.4810091.0310091.0310102.2910121.05
10144.0110177.7010226.8910247.6210260.2310272.8510276.0810282.04
   50.57   50.46   49.88   49.57   49.13   48.12   47.38   47.19   47.08   46.90
   46.95   46.89   47.07   47.16   47.16   47.64   48.79   48.79   49.17   49.42
   49.92   51.09   54.04   55.06   55.27   56.07   56.37   56.74
 -949.43 -949.54 -950.12 -950.43 -950.87 -951.88 -952.62 -952.81 -952.92 -953.10
 -953.05 -953.11 -952.93 -952.84   44.16   44.64   45.79 -951.21 -950.83 -950.58
 -950.08 -948.91 -945.96 -944.94 -944.73 -943.93 -943.63 -943.26
 9678.30 9686.18 9701.72 9713.53 9737.14 9772.56 9807.97 9819.78 9843.39 9855.19
 9878.80 9890.61 9907.83 9907.8310056.8310056.8310083.4810091.1810102.2910121.05
10144.0110171.9110184.5310226.8910247.6210260.2310272.8510276.0810282.04
   50.57   50.46   49.88   49.57   49.13   48.12   47.38   47.19   47.08   46.90
   46.95   46.89   47.01   47.01   47.55   47.55   47.64   48.81   49.17   49.42
   49.92   50.85   51.45   54.04   55.06   55.27   56.07   56.37   56.74
 -949.43 -949.54 -950.12 -950.43 -950.87 -951.88 -952.62 -952.81 -952.92 -953.10
 -953.05 -953.11 -952.99   44.01   44.55 -952.45 -952.36 -951.19 -950.83 -950.58
 -950.08 -949.15 -948.55 -945.96 -944.94 -944.73 -943.93 -943.63 -943.26
Pier Skew, UpSta & Num, DnSta & Num=  ,9991.20, 2 ,9957.00, 2 , 0 , 0 , 0 ,,
    3.00    3.00
 -952.68   47.32
    3.00    3.00
 -952.79   47.21
Pier Skew, UpSta & Num, DnSta & Num=  ,10041.86, 2 ,10007.66, 2 , 0 , 0 , 0 ,,
    3.00    3.00
 -952.50   47.50
    3.00    3.00
 -952.62   47.38
BR Coef=-1 , 0 , 0 ,, 0 ,,,0.8,0,1,0,
WSPro=,,,, 1 ,,,, 0 ,,,, 0 ,,,,-1 ,-1 ,-1 , 0 , 0 , 0 , 0 , 0
BC Design=,, 0 ,, 0 ,,,,,,

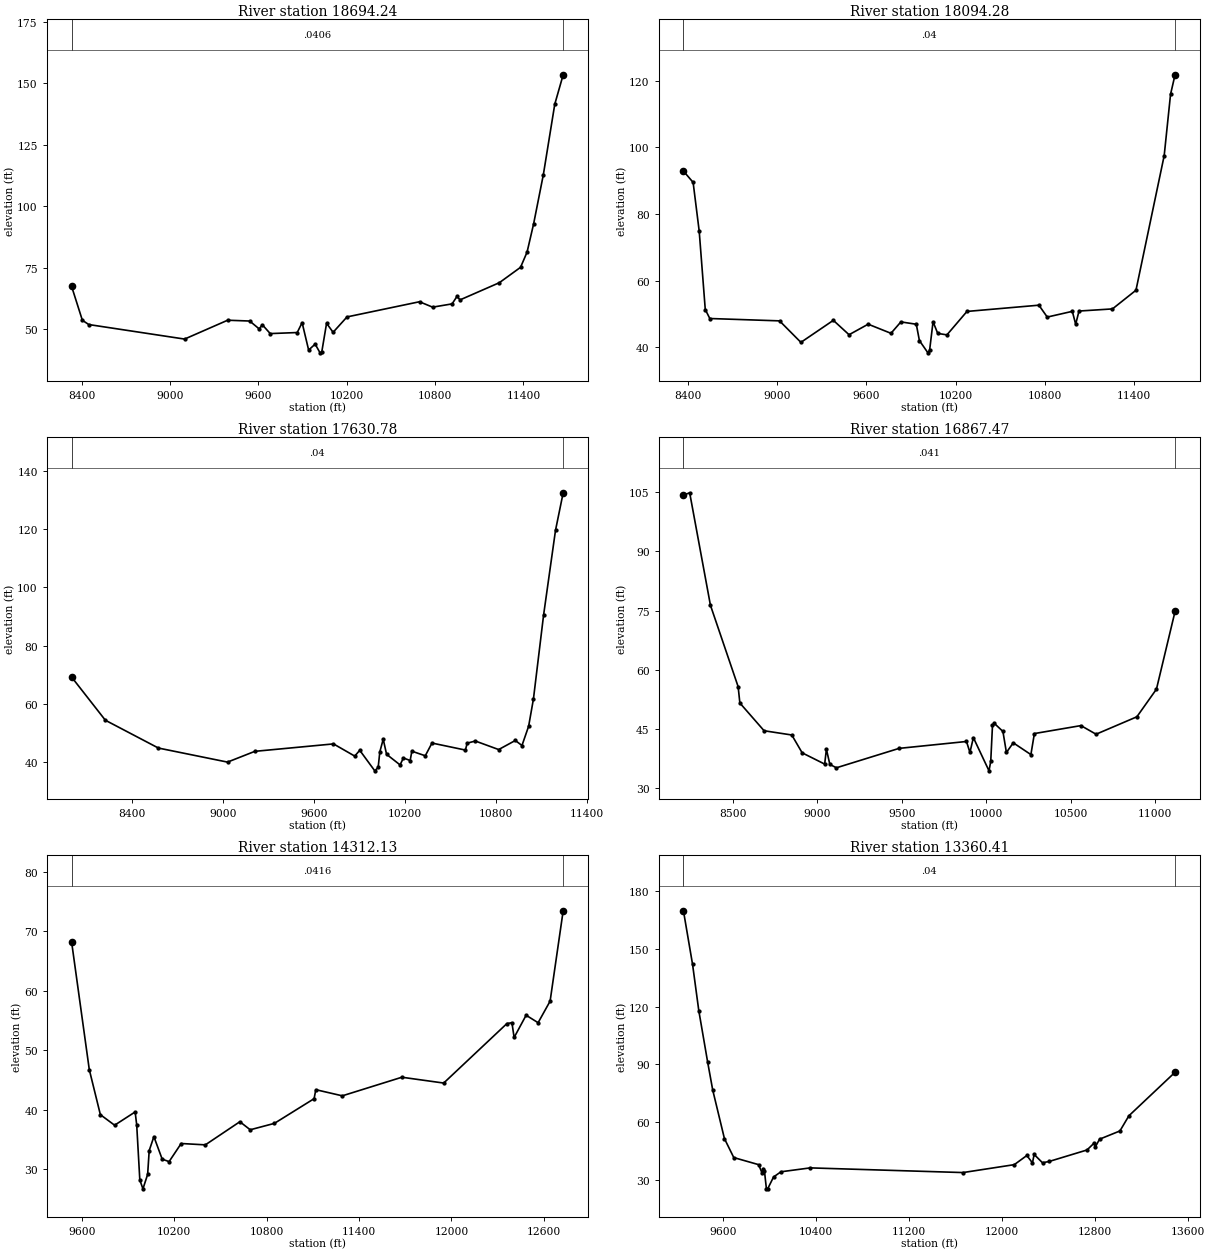
Type RM Length L Ch R = 1 ,18694.24,599.962100,599.962100,599.962100
XS GIS Cut Line= 6
833004.550075065721902.179939964832897.794353041721659.332570173
832729.740641933721256.130525667832557.416491993 720831.53713393
832445.920253535720538.343520052831642.292892531718854.453523065
#Sta/Elev= 30
8330.67667.559288404.06153.735618447.75551.998899098.56346.102689391.06653.75898
9540.935 53.4291 9605.3150.241289626.76851.915089680.41348.32814  9863.848.75716
9897.03352.765429941.34341.648829985.65344.0523610018.8940.5124210029.96 40.6511
 10063.252.5310710107.5148.8446110202.0155.0990810694.5461.2633410783.6259.06669
10915.9960.3965210949.2163.4340510969.9662.0189311237.0869.0012811381.0275.24415
11425.3181.40918 11469.6 92.826211536.04   112.911613.54141.484511670.63153.4405
#Mann= 3 , 0 , 0
8330.676  0.0406       08330.676  0.0406       011670.63  0.0406       0
#XS Ineff= 2 , 0
       08626.628        10067.62       0
Bank Sta=8330.676,11670.63
Exp/Cntr=0.3,0.1

Type RM Length L Ch R = 1 ,18094.28,463.498100,463.498100,463.498100
XS GIS Cut Line= 6
833375.831830583721688.619655292833225.493341509720932.075781087
 833104.17004253720533.896824924 832987.69247224720273.715039543
 832761.54223399719858.025125976832140.830740133718652.650530221
#Sta/Elev= 30
8372.00392.872048437.03189.475378477.91674.838858518.64151.307638549.16748.60306
9017.58747.895939161.03141.441679378.913 48.05489484.48243.733839612.89746.89589
 9766.07 44.16069832.59347.582719936.14746.883199957.006 41.980210014.2738.29615
10025.7139.1160310048.6147.62128 10080.244.1289410141.8443.6885610276.4550.72713
10759.6352.6029810815.77 49.033910984.1950.7548811006.6446.88085 11029.150.84418
11253.8451.4853311411.6657.0893111601.2597.5073311643.94115.915211674.18121.7798
#Mann= 3 , 0 , 0
8372.003    0.04       08372.003    0.04       011674.18    0.04       0
#XS Ineff= 2 , 0
       08586.448        10275.37       0
Bank Sta=8372.003,11674.18
Exp/Cntr=0.3,0.1

Type RM Length L Ch R = 1 ,17630.78,763.305400,763.305400,763.305400
XS GIS Cut Line= 6
 834005.25060891721805.265878779833433.869803397720174.994519919
833409.469979306720111.737761088833340.231843055719955.029622192
833105.329594825719463.238257937832804.142195223718797.400812387
#Sta/Elev= 30
7998.82369.216418221.74554.38584 8571.6144.84502 9027.4940.023129207.72243.71557
9726.36146.266489866.61842.080939899.54744.073399998.80837.0266310021.0338.20674
10032.1443.5602810054.3647.8794710076.5842.7003910165.4739.0621310187.6941.44092
10232.1340.5615510243.2443.7645510331.8342.1964810376.0246.56041 10596.4  44.152
10608.3846.5334110662.2547.2507610815.9144.3270910925.6647.4402610969.5745.71384
11013.4752.3267711045.1361.6562111112.2590.5124211190.71119.523411241.32132.4197
#Mann= 3 , 0 , 0
7998.823    0.04       07998.823    0.04       011241.32    0.04       0
#XS Ineff= 2 , 0
       08533.269        10387.67       0
Bank Sta=7998.823,11241.32
Exp/Cntr=0.3,0.1

Type RM Length L Ch R = 1 ,16867.47,2555.345900,2555.345900,2555.345900
XS GIS Cut Line= 6
834442.543024779721481.059212043834097.153967091719935.764061846
834073.939826242719814.528378392834029.173902153719628.695386374
833915.355072079719223.867455259833731.984972586718660.953838008
#Sta/Elev= 30
8208.128104.22488245.077104.83148368.03876.329658531.98655.712258542.232 51.5668
8685.68744.538988849.63443.463128911.115 38.94289044.32336.090279054.56939.85557
9075.06336.013269113.75735.152589484.93240.073079883.965 41.81849904.32839.04927
9924.76642.7927110017.3234.3813110027.6136.80185 10037.945.90322 10048.2 46.4254
10099.6544.3654110120.3239.0317410160.9441.4809310265.2538.4976710285.9643.82659
10561.4845.84252 10651.243.6583710892.7548.0744611008.6655.0771711118.76 74.7651
#Mann= 3 , 0 , 0
8208.128   0.041       08208.128   0.041       011118.76   0.041       0
#XS Ineff= 2 , 0
       08933.252        10070.71       0
Bank Sta=8208.128,11118.76
Exp/Cntr=0.3,0.1

Type RM Length L Ch R = 1 ,14312.13,951.717800,951.717800,951.717800
XS GIS Cut Line= 6
835619.204456647721127.081910933835530.437634445720753.606025177
835501.125358567720585.140777112  835006.7549188719610.525098554
834572.400497627719315.273483198833789.710701375718660.540398882
#Sta/Elev= 30
9532.98868.254099648.19246.736569720.14239.168169812.649 37.39799945.94139.62437
9956.105 37.46899976.43228.173859996.759 26.702610027.1829.1331710037.3233.13446
10067.7335.4764710121.6731.6922910166.5231.2769610245.0134.3222710401.9934.09486
10626.2537.9839210693.52   36.6310850.51 37.7067 11108.441.8577711119.6243.36917
11291.6442.3366411678.5745.4622711950.2244.4843512360.9254.48416 12393.554.63161
12407.6752.14151 12485.655.8830712563.53 54.627112641.4558.2507112726.3373.44191
#Mann= 3 , 0 , 0
9532.988  0.0416       09532.988  0.0416       012726.33  0.0416       0
#XS Ineff= 2 , 0
       09858.842        10582.18       0
Bank Sta=9532.988,12726.33
Exp/Cntr=0.3,0.1

Type RM Length L Ch R = 1 ,13360.41,1125.626400,1125.626400,1125.626400
XS GIS Cut Line= 6
836621.793513506 720758.81606321836572.413989439720626.192505149
836500.687358421720468.280257781836377.967666443720261.260182868
836081.387414055719874.014553677834311.500734998 717224.92399975
#Sta/Elev= 30
9257.212169.78399335.744141.92099389.316117.89899465.38491.161949509.28176.56938
9609.92551.34721 9690.3541.485619904.28237.804289931.70333.713369944.18335.75784
9954.42834.41835 9970.9425.335079981.88225.2321510032.6431.3983410096.2134.09831
10347.8236.1247311662.4533.6920712103.6937.8025112211.9342.5660312260.0338.69292
12274.4843.1254412346.4838.7795812404.3539.4771312729.0745.42759 12789.248.92849
12801.2347.0771212837.3151.0409913012.5155.3243213089.8663.2161513486.8385.83417
#Mann= 3 , 0 , 0
9257.212    0.04       09257.212    0.04       013486.83    0.04       0
#XS Ineff= 2 , 0
       0                10884.87       0
Bank Sta=9257.212,13486.83
Exp/Cntr=0.3,0.1

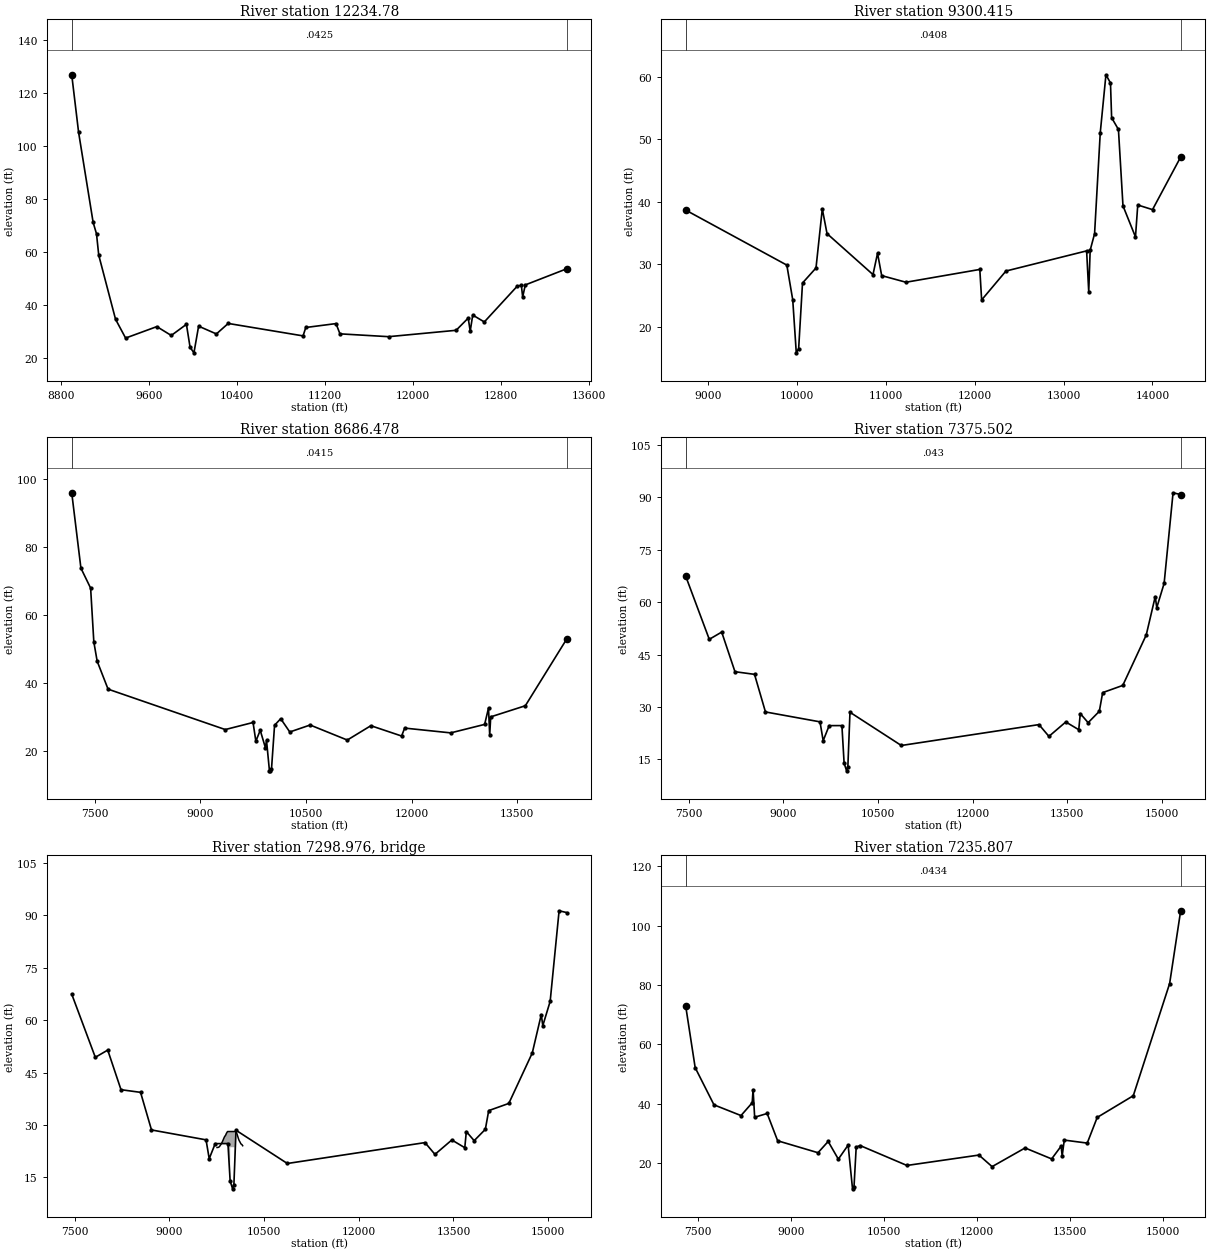
Type RM Length L Ch R = 1 ,12234.78,2934.368900,2934.368900,2934.368900
XS GIS Cut Line= 6
837139.110837614720546.585380765837258.841896686 719859.03132315
837271.731143342719682.596167659837247.225889884719588.134302472
   837212.486394 719506.01832231835335.851703598716630.047495777
#Sta/Elev= 30
8898.394126.98688960.753105.28729092.94771.294969123.45366.996659143.79158.93974
9296.32234.784179387.84127.677149671.51431.99906  9802.728.661429940.33132.85816
9973.69324.1898410008.6622.1073910051.0532.1685810212.64 29.235610320.1133.19424
11000.08 28.498111024.6931.6659211299.3533.1407711335.1829.2706111777.0328.20426
12390.4630.6091112500.2335.2122212518.5230.2770612541.3136.3602912646.5833.75883
12947.3447.3274212983.1647.51625 12995.143.1944713018.9947.72968 13395.153.80952
#Mann= 3 , 0 , 0
8898.394  0.0425       08898.394  0.0425       0 13395.1  0.0425       0
#XS Ineff= 2 , 0
       0                11355.33       0
Bank Sta=8898.394,13395.1
Exp/Cntr=0.3,0.1

Type RM Length L Ch R = 1 ,9300.415,613.937500,613.937500,613.937500
XS GIS Cut Line= 5
839063.713697052720487.928306276838969.742950808720379.201008803
838844.901844375  720243.9718821837913.985592684719181.685386171
835531.172800789716187.343136068
#Sta/Elev= 30
8750.68638.672249888.15629.848139954.63824.285389994.52715.7754110021.1216.44308
10064.5226.9755810216.2529.3887710287.0538.8612110340.2434.9005210857.2828.32733
 10908.4 31.750610955.0128.16191 11227.927.0997512058.5929.1542212079.1924.26196
12352.53  28.896 13259.932.1295913283.6725.5761413299.7332.2256913349.3634.88175
13413.2651.0833613477.1660.3771613528.2859.0648413541.0653.4973613617.7451.60078
13668.8639.3552613809.4434.36604   1383539.4908914001.1338.7484714317.6447.18488
#Mann= 3 , 0 , 0
8750.686  0.0408       08750.686  0.0408       014317.64  0.0408       0
#XS Ineff= 2 , 0
       0                12227.16       0
Bank Sta=8750.686,14317.64
Exp/Cntr=0.3,0.1

Type RM Length L Ch R = 1 ,8686.478,1310.976500,1310.976500,1310.976500
XS GIS Cut Line= 6
840408.349931165721144.629012747839605.373921997 720199.63051337
  839255.3192812719807.171114837838842.532619063719367.678440795
838763.520867194719275.734886295835643.251923521 715978.34341747
#Sta/Elev= 30
7172.81696.074797303.29773.835537441.26567.938937486.65152.079887534.18146.37582
 7689.0438.132059353.36126.212639748.12728.299239787.90422.77476 9849.9726.00156
9922.71520.907189939.34722.992449980.91214.043269994.41714.0328510010.0114.55239
10053.6627.4927410140.9529.4123110269.7725.4968610558.8927.5531311086.6423.11698
11421.2727.3501611857.7424.3080111901.3926.6451112555.1825.2320913037.0527.73432
13092.1232.5502413108.9624.6470713123.51 29.959213615.2833.2389114202.6852.92385
#Mann= 3 , 0 , 0
7172.816  0.0415       07172.816  0.0415       014202.68  0.0415       0
#XS Ineff= 2 , 0
       09730.465        12116.41       0
Bank Sta=7172.816,14202.68
Exp/Cntr=0.3,0.1

Type RM Length L Ch R = 1 ,7375.502,139.694500,139.694500,139.694500
XS GIS Cut Line= 6
841225.443324222 720715.67727831840038.070184844719089.619930662
839710.037517837718581.411333751839566.843247558718408.627108875
839302.790093675718185.518775778835462.460327651715556.922257367
#Sta/Elev= 30
7452.72867.456517826.53549.363418023.15351.435618233.50440.08858 8543.2139.33155
8716.56228.564249580.81825.727919630.95820.334539726.22824.646149927.94524.65578
9962.76213.8798210002.49 11.697110022.19 12.926110055.6128.4759910869.0418.95607
13050.3124.9407613207.8521.56757 13475.125.6935313680.4623.47832 13704.728.09817
13829.1925.4891914006.2328.7465214059.3534.0975714378.0336.1615514749.8250.61233
14892.2861.5967514916.5158.4342315033.09 65.383215174.73 91.330715295.2590.82007
#Mann= 3 , 0 , 0
7452.728   0.043       07452.728   0.043       015295.25   0.043       0
#XS Ineff= 2 , 0
       09932.976        12842.71       0
Bank Sta=7452.728,15295.25
Exp/Cntr=0.3,0.1

Type RM Length L Ch R = 3 ,7298.976,,,
BEGIN DESCRIPTION:
END DESCRIPTION:
Bridge Culvert--1,0,-1,-1, 0
Deck Dist Width WeirC Skew NumUp NumDn MinLoCord MaxHiCord MaxSubmerge Is_Ogee
57.847250,24.000000,2.6,0, 46, 46, , , 0.95, 0, 0,0,,
 9755.59 9756.74 9768.70 9772.45 9780.66 9790.68 9792.62 9804.58 9808.92 9816.54
 9827.15 9828.50 9840.45 9845.39 9847.05 9852.32 9864.08 9864.32 9875.84 9883.33
 9887.60 9899.36 9902.33 9911.12 9920.93 9962.94 9962.9410033.9410033.9410050.71
10058.6710069.9710070.8310081.2710092.3210092.5710103.8710104.7510112.5810115.68
10127.5410131.1810139.4010149.7810151.2610161.32
   23.54   23.55   23.55   23.57   23.64   23.74   23.77   24.09   24.22   24.39
   24.75   24.79   25.22   25.45   25.50   25.72   26.24   26.25   26.69   26.87
   26.93   27.40   27.56   27.80   28.11   28.11   28.11   28.11   28.11   28.12
   27.82   27.47   27.44   26.84   26.18   26.17   25.60   25.56   25.30   25.21
   24.79   24.63   24.49   24.36   24.32   24.04
 -976.46 -976.45 -976.45 -976.43 -976.36 -976.26 -976.23 -975.91 -975.78 -975.61
 -975.25 -975.21 -974.78 -974.55 -974.50 -974.28 -973.76 -973.75 -973.31 -973.13
 -973.07 -972.60 -972.44 -972.20 -971.89 -971.89   23.61   23.61 -971.89 -971.88
 -972.18 -972.53 -972.56 -973.16 -973.82 -973.83 -974.40 -974.44 -974.70 -974.79
 -975.21 -975.37 -975.51 -975.64 -975.68 -975.96
 9755.59 9756.74 9768.70 9772.45 9780.66 9790.68 9792.62 9804.58 9808.92 9816.54
 9827.15 9828.50 9840.45 9845.39 9847.05 9852.32 9864.08 9864.32 9875.84 9883.33
 9887.60 9899.36 9902.33 9911.12 9920.93 9948.92 9948.9210019.9210019.9210050.71
10058.6710069.9710070.8310081.2710092.3210092.5710103.8710104.7510112.5810115.68
10127.5410131.1810139.4010149.7810151.2610161.32
   23.54   23.55   23.55   23.57   23.64   23.74   23.77   24.09   24.22   24.39
   24.75   24.79   25.22   25.45   25.50   25.72   26.24   26.25   26.69   26.87
   26.93   27.40   27.56   27.80   28.11   28.11   28.11   28.11   28.11   28.12
   27.82   27.47   27.44   26.84   26.18   26.17   25.60   25.56   25.30   25.21
   24.79   24.63   24.49   24.36   24.32   24.04
 -976.46 -976.45 -976.45 -976.43 -976.36 -976.26 -976.23 -975.91 -975.78 -975.61
 -975.25 -975.21 -974.78 -974.55 -974.50 -974.28 -973.76 -973.75 -973.31 -973.13
 -973.07 -972.60 -972.44 -972.20 -971.89 -971.89   23.61   23.61 -971.89 -971.88
 -972.18 -972.53 -972.56 -973.16 -973.82 -973.83 -974.40 -974.44 -974.70 -974.79
 -975.21 -975.37 -975.51 -975.64 -975.68 -975.96
BR Coef=-1 , 0 , 0 ,, 0 ,,,0.8,0,1,0,
WSPro=,,,, 1 ,,,, 0 ,,,, 0 ,,,,-1 ,-1 ,-1 , 0 , 0 , 0 , 0 , 0
BC Design=,, 0 ,, 0 ,,,,,,

Type RM Length L Ch R = 1 ,7235.807,537.420700,537.420700,537.420700
XS GIS Cut Line= 6
841478.190423874720696.714047597839938.880039828718692.881790193
839802.008159728718475.791545145839687.864553705718341.946394288
839587.896101208 718258.02401417835627.524350276715390.249223863
#Sta/Elev= 30
7300.675  72.9287453.64952.174767756.79439.652658192.33736.044778372.90540.34744
8387.29144.782458412.51135.48408 8614.2736.746298783.28727.555379433.91623.53371
9597.84527.330839761.77421.365319919.56426.101949990.49411.3732110014.1411.99695
 10049.625.3990210111.4625.9633610867.3719.2469412028.6922.7476612240.6118.85117
12772.59 25.140713200.6521.4507513353.5125.74772 13370.522.4548413404.47 27.7863
13774.6826.7750113935.51 35.424414516.9742.7248615102.9680.5026115280.88104.9989
#Mann= 3 , 0 , 0
7300.675  0.0434       07300.675  0.0434       015280.88  0.0434       0
#XS Ineff= 2 , 0
       09920.266        12863.29       0
Bank Sta=7300.675,15280.88
Exp/Cntr=0.3,0.1

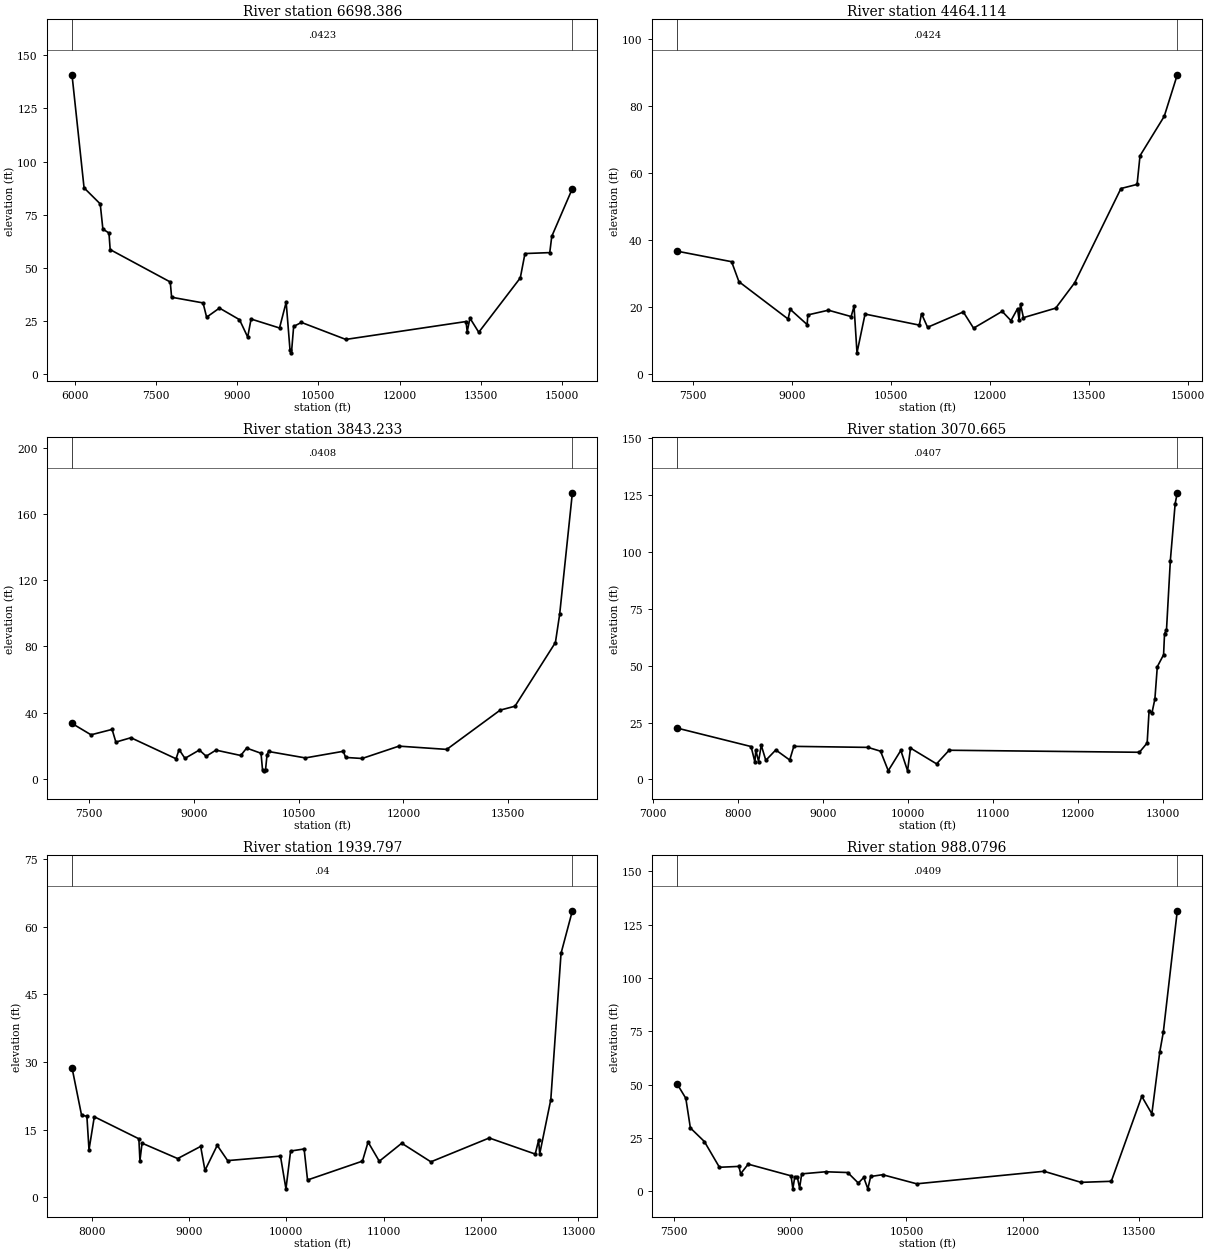
Type RM Length L Ch R = 1 ,6698.386,2234.271900,2234.271900,2234.271900
XS GIS Cut Line= 6
842654.004467194721424.183092043840433.293519594718420.605200856
840117.713506314718053.029523795840017.745137583717969.106376744
839862.234675817717872.719890958836057.374451262715101.302695426
#Sta/Elev= 30
5950.131140.83476172.97187.657226471.44580.112166520.35868.264486633.11966.41341
6654.92358.622157764.83343.386757789.70636.215658370.62833.54189  8436.426.82201
8673.39931.118949043.45325.659859194.839 17.49389257.20425.966299782.781 21.7507
9905.30133.873429976.61611.3369910003.0210.0647410043.6722.4810410187.4324.36686
11006.5916.3746913226.99 24.786713248.5820.0355413299.5326.3887513462.05 19.7308
14229.09 45.295114315.6956.7618914773.4357.2007114810.5564.8486215191.1387.34555
#Mann= 3 , 0 , 0
5950.131  0.0423       05950.131  0.0423       015191.13  0.0423       0
#XS Ineff= 2 , 0
       0 9888.51        12904.91       0
Bank Sta=5950.131,15191.13
Exp/Cntr=0.3,0.1

Type RM Length L Ch R = 1 ,4464.114,620.881500,620.881500,620.881500
XS GIS Cut Line= 2
842970.888912415718230.817682987836146.595161984714945.591663867
#Sta/Elev= 30
7261.70436.595898089.52233.437568200.50627.46228  8944.116.315448977.39519.19597
9232.65814.651729243.757 17.53589554.512  18.9429898.56317.043789942.95720.08728
 9987.356.20130410109.4317.7880610930.7214.4866510964.01 17.894711056.0313.84021
11596.6218.42304   1175213.5723712184.8418.5971412318.0215.82065 12417.919.41321
 12440.116.0170212462.3520.7649412506.69 16.719212995.0219.5589413283.5827.17251
13982.7855.3118914226.9456.5355314271.3465.1043414637.5976.8686414835.5989.29739
#Mann= 3 , 0 , 0
7261.704  0.0424       07261.704  0.0424       014835.59  0.0424       0
#XS Ineff= 2 , 0
       0 8931.69        12418.37       0
Bank Sta=7261.704,14835.59
Exp/Cntr=0.3,0.1

Type RM Length L Ch R = 1 ,3843.233,772.568200,772.568200,772.568200
XS GIS Cut Line= 6
843107.954035399717469.347480113840648.026835711716478.804570556
 840595.89691374716461.180075758840540.103331913716439.907673985
840318.626142616716348.184540926 836612.53719512714454.393042126
#Sta/Elev= 30
7251.57533.390367524.26726.497617826.11529.766857880.01622.094028095.62224.73321
8742.43911.98698 8785.5617.582298869.52812.239049076.62717.29822 9173.6513.50831
9313.79317.227719669.54313.98127    975318.465169959.43315.326029980.7995.378841
   100014.69132510023.715.19045610045.3614.2595710067.0116.3995710594.5512.51027
11137.9116.52306 11171.612.8006811407.6912.1703611935.2419.6417912620.2717.66851
13385.59 41.440113597.2743.7960814176.7582.3499214237.3899.3428914419.82172.9866
#Mann= 3 , 0 , 0
7251.575  0.0408       07251.575  0.0408       014419.82  0.0408       0
#XS Ineff= 2 , 0
       08769.192        11782.42       0
Bank Sta=7251.575,14419.82
Exp/Cntr=0.3,0.1

Type RM Length L Ch R = 1 ,3070.665,1130.867300,1130.867300,1130.867300
XS GIS Cut Line= 6
843227.182450981716832.233636846843024.134321501716755.594723285
  842876.7136025716702.391768119 842605.54678362716609.436139175
842038.228293423716396.557771293837973.072264699714203.386262093
#Sta/Elev= 30
7284.02422.577318156.318  14.4538201.3657.6441068212.04612.984188244.0887.883001
8276.13115.023588329.5358.4028288447.02412.957588610.8658.543588 8658.9714.53405
9531.228 14.08299678.94112.418679769.841 3.847979917.55312.748839997.0913.794102
10031.1813.7860210337.976.86258410485.6812.8298112723.7411.9402812814.9916.01844
12837.72 30.2422 12871.829.2846112905.8935.3068712934.3549.4902413008.1554.73068
13019.5264.0478113042.2465.5040113087.6996.06563 13144.5121.087813169.42125.7948
#Mann= 3 , 0 , 0
7284.024  0.0407       07284.024  0.0407       013169.42  0.0407       0
#XS Ineff= 2 , 0
       08377.554        11538.87       0
Bank Sta=7284.024,13169.42
Exp/Cntr=0.3,0.1

Type RM Length L Ch R = 1 ,1939.797,951.717800,951.717800,951.717800
XS GIS Cut Line= 6
843425.293345616 716037.00628541842295.605313758715544.782945973
841722.266996404715263.518041822 841532.42812745 715146.45115408
841390.798142079715037.210468363838903.871048366713615.023308492
#Sta/Elev= 30
7799.74628.737517898.10718.157957952.57417.949267974.36110.500098028.82917.83588
8486.354  12.9428497.2488.0981438519.03511.968338884.7138.5526039120.93111.24846
9165.0475.920894 9290.9711.487749397.8758.0998279940.2659.0980569996.6281.832224
10044.4710.2235510183.1510.6804210218.263.79899910782.177.98394910839.7712.22284
10954.977.96017111185.3611.9558811484.877.828499 12083.913.12142 12556.2 9.55168
12590.7612.6191312602.289.60447312716.1221.6349912821.1654.1009412937.6563.55641
#Mann= 3 , 0 , 0
7799.746    0.04       07799.746    0.04       012937.65    0.04       0
#XS Ineff= 2 , 0
       08619.393         11283.1       0
Bank Sta=7799.746,12937.65
Exp/Cntr=0.3,0.1

Type RM Length L Ch R = 1 ,988.0796,988.079600,988.079600,988.079600
XS GIS Cut Line= 6
844075.512960753715468.804488407841967.029614092714307.414484945
841926.969221039714271.295921849841925.454907588714269.989455315
841832.527087255 714186.52989263838489.013537996712239.768259882
#Sta/Elev= 30
7537.87950.529457652.63143.668757711.57829.76564 7892.3823.383818086.46411.32701
 8337.6311.733978360.4638.2969498457.741 12.78319011.2137.3109059034.0461.218856
9058.8166.7600239091.1296.8043659120.9961.6132849148.2138.2374249456.4629.217628
9741.8798.8621749878.8783.9233159948.6676.54624110001.611.242553 10038.47.004816
10192.477.83891310632.19 3.5758212275.369.446677 12752.34.26188313143.23 4.75158
13536.6644.57146 13666.536.3812913768.0965.2138413814.3874.6347813994.88131.5422
#Mann= 3 , 0 , 0
7537.879  0.0409       07537.879  0.0409       013994.88  0.0409       0
#XS Ineff= 2 , 0
       08729.618        10809.08       0
Bank Sta=7537.879,13994.88
Exp/Cntr=0.3,0.1

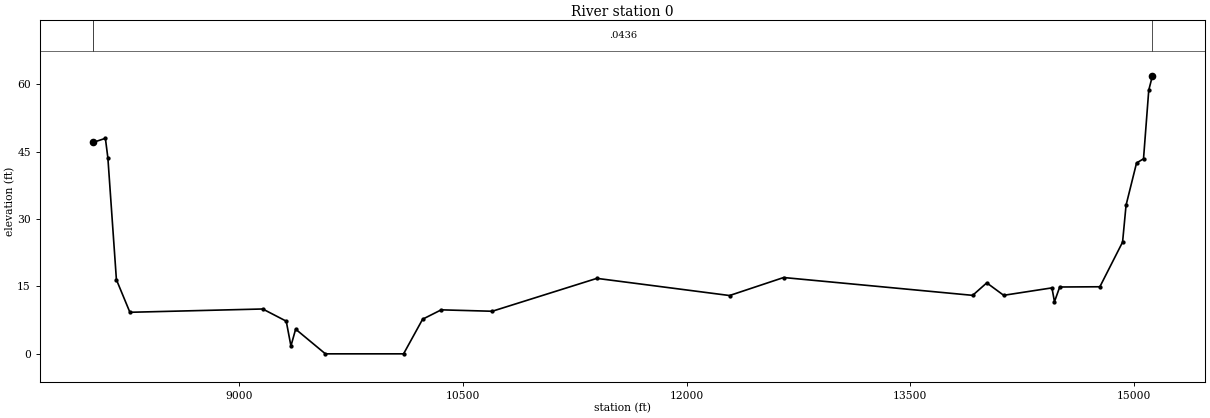
Type RM Length L Ch R = 1 ,       0,0.000000,0.000000,0.000000
XS GIS Cut Line= 6
844405.282402235714287.038121911842667.976580528713610.435108055
841361.906999736712878.509527354839573.912320367711424.448197101
839063.373715955710893.492278932838473.870495997710534.702663062
#Sta/Elev= 30
8021.07647.057758103.61347.973538120.32743.617588177.54516.479368268.0239.216653
 9158.549.9518629316.1497.2389219347.6711.7089459379.1935.4594539578.831-0.04068
10102.89-0.0406810230.637.67768610355.339.76191510697.329.44665211398.8616.77373
12288.4912.94984 12651.116.96093 13918.312.9885414012.94 15.769914126.3912.99939
14450.0214.65537 14466.911.5724514502.0214.8496914771.2714.9025914923.4624.84528
14946.87 33.076915017.1142.4749615063.9343.4143315099.0558.6997815123.7961.90705
#Mann= 3 , 0 , 0
8021.076  0.0436       08021.076  0.0436       015123.79  0.0436       0
#XS Ineff= 2 , 0
       09225.709        10237.72       0
Bank Sta=8021.076,15123.79
Exp/Cntr=0.3,0.1